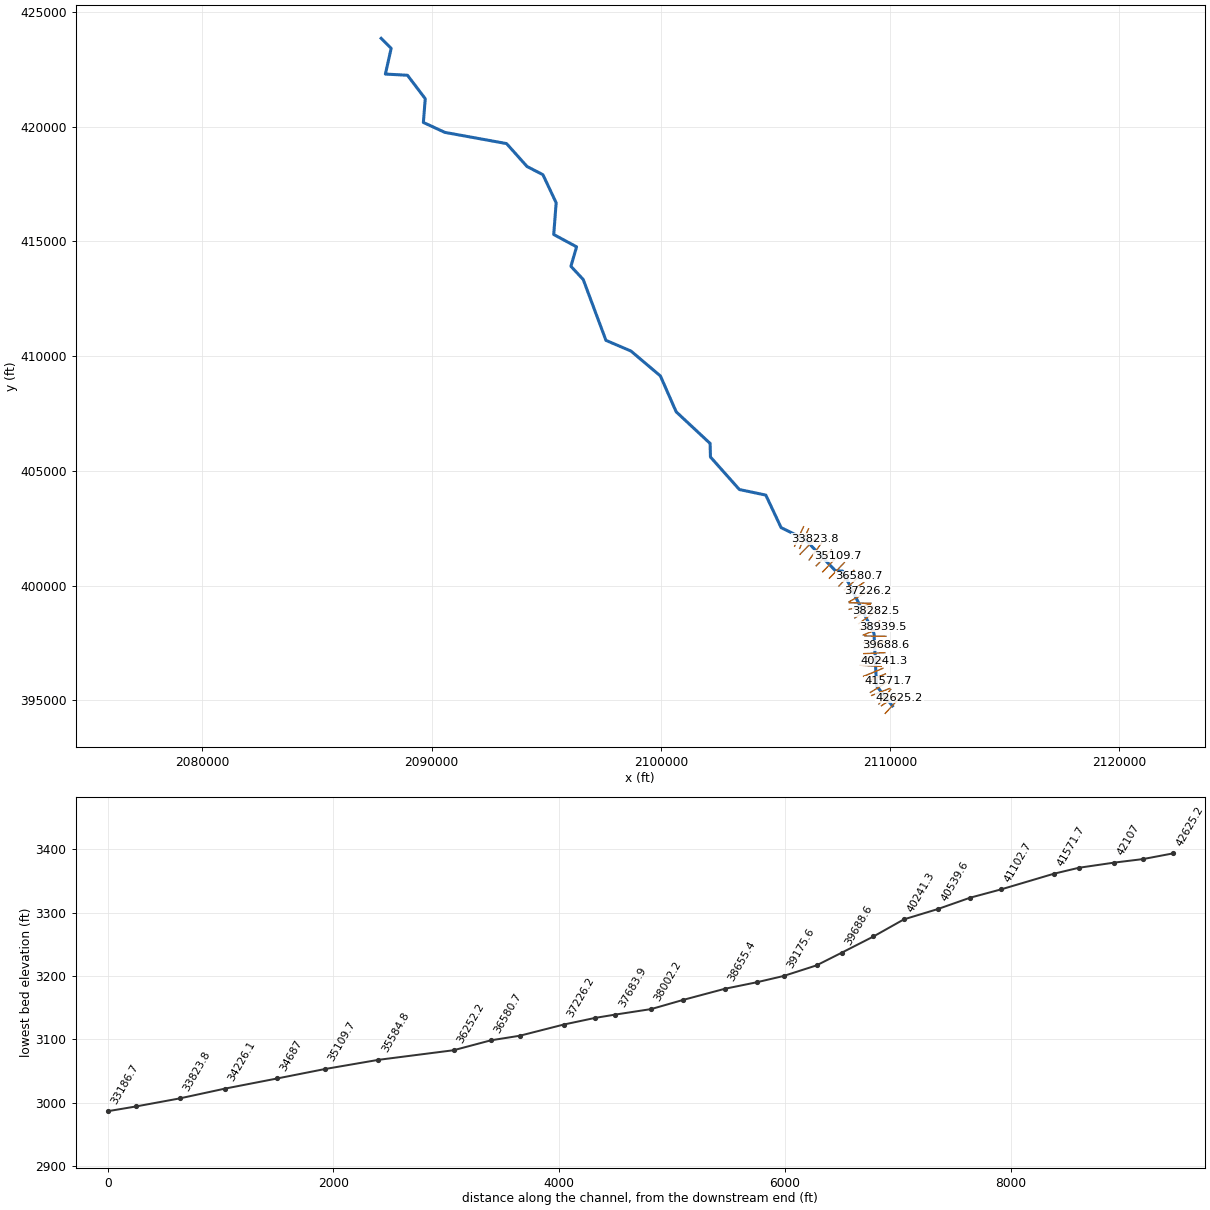
--- LaurCk.prj (project) ---

Proj Title=LaurCk
Current Plan=p01
Default Exp/Contr=0,0
English Units
Geom File=g01
Flow File=f01
Plan File=p01
BEGIN DESCRIPTION:
END DESCRIPTION:
DSS Export Rating Curves= 0
DSS Export Rating Curve Sorted= 0
DSS Export Volume Flow Curves= 0
DXF OffsetX= 0
DXF OffsetY= 0
DXF ScaleX= 0
DXF ScaleY= 0

--- LaurCk.p01 (plan) ---

Plan Title=Floodplain
Program Version=4.00
Geom File=g01
Flow File=f01
K Sum by GR=0
Std Step Tol=0.01
Critical Tol=0.01
Num of Std Step Trials=20
Max Error Tol=0.3
Flow Tol Ratio=0.001
Split Flow NTrial=30
Split Flow Tol=0.02
Split Flow Ratio=0.02
Log Output Level=0
Friction Slope Method=1
Unsteady Friction Slope Method=2
Unsteady Bridges Friction Slope Method=1
Global Log Level=0
CheckData=False
Run HTab=0
Run UNet=0
Run PostProcess=0
UNET Theta=0
UNET Theta Warmup=0
UNET ZTol=0
UNET ZSATol=0
UNET MxIter=0
UNET MaxInSteps=0
UNET DtIC=0
UNET DtMin=0
UNET MaxCRTS=0
UNET WFStab=0
UNET SFStab=0
UNET WFX=0
UNET SFX=0
UNET DSS MLevel=0
UNET DZMax Abort=0
UNET Convert EG Bridges=0
UNET Use Existing IB Tables=0
UNET Froude Limit=0
UNET Froude Power=0
Write IC File=0
Echo Input=False
Echo Output=False
Write Detailed=0

--- LaurCk.f01 (steady flow) ---

Flow Title=NFF Regression Equation
Program Version=4.00
Number of Profiles=1
Profile Names=P100yr
River Rch & RM=LaurCk,Main      ,42625.2
531.5361
River Rch & RM=LaurCk,Main      ,42107
590.3180
River Rch & RM=LaurCk,Main      ,39175.6
651.5766
River Rch & RM=LaurCk,Main      ,38939.5
722.8619
River Rch & RM=LaurCk,Main      ,36580.7
760.6633
River Rch & RM=LaurCk,Main      ,36252.2
945.0779
River Rch & RM=LaurCk,Main      ,30856.5
1017.338
River Rch & RM=LaurCk,Main      ,30362.1
1532.993
River Rch & RM=LaurCk,Main      ,29843.1
1536.145
River Rch & RM=LaurCk,Main      ,29307.7
1926.233
River Rch & RM=LaurCk,Main      ,28251.2
1941.107
River Rch & RM=LaurCk,Main      ,23420.7
2156.639
River Rch & RM=LaurCk,Main      ,23249.5
2554.575
River Rch & RM=LaurCk,Main      ,22563.5
2817.655
River Rch & RM=LaurCk,Main      ,19540.1
2986.984
River Rch & RM=LaurCk,Main      ,19151.7
3334.310
River Rch & RM=LaurCk,Main      ,8232.9
3700.646
River Rch & RM=LaurCk,Main      ,5894.3
4106.242
River Rch & RM=LaurCk,Main      ,3243.4
4331.440
River Rch & RM=LaurCk,Main      ,146.1
4792.349
Boundary for River Rch & Prof#=LaurCk,Main      ,1
Up Type=0
Dn Type=3
Dn Slope=0.005146

--- LaurCk.g01 (geometry) ---

Geom Title=USGS 10m DEM
Program Version=4.10

River Reach=LaurCk          ,Main
Reach XY= 30
      2110103.94      394749.726     2109411.651      395623.885
     2109300.559      397909.499     2107929.871      400629.082
     2107615.347      400645.789     2106284.611      402020.108
     2105248.786      402522.766     2104581.516      403942.657
     2103427.237      404185.265     2102166.384      405603.241
     2102150.929      406194.387     2100671.208      407572.858
     2099982.052      409138.006     2098695.291      410224.124
     2097607.515      410688.419     2096616.531      413340.205
     2096079.432      413918.224     2096326.126      414766.087
     2095329.768      415303.386     2095435.443      416686.621
     2094857.935      417911.641     2094163.891      418268.376
     2093271.852      419267.928     2090580.558      419755.904
     2089642.739      420188.673     2089725.084      421223.477
      2088949.21      422246.386     2087985.878      422298.304
     2088238.605      423419.147     2087799.968      423856.007

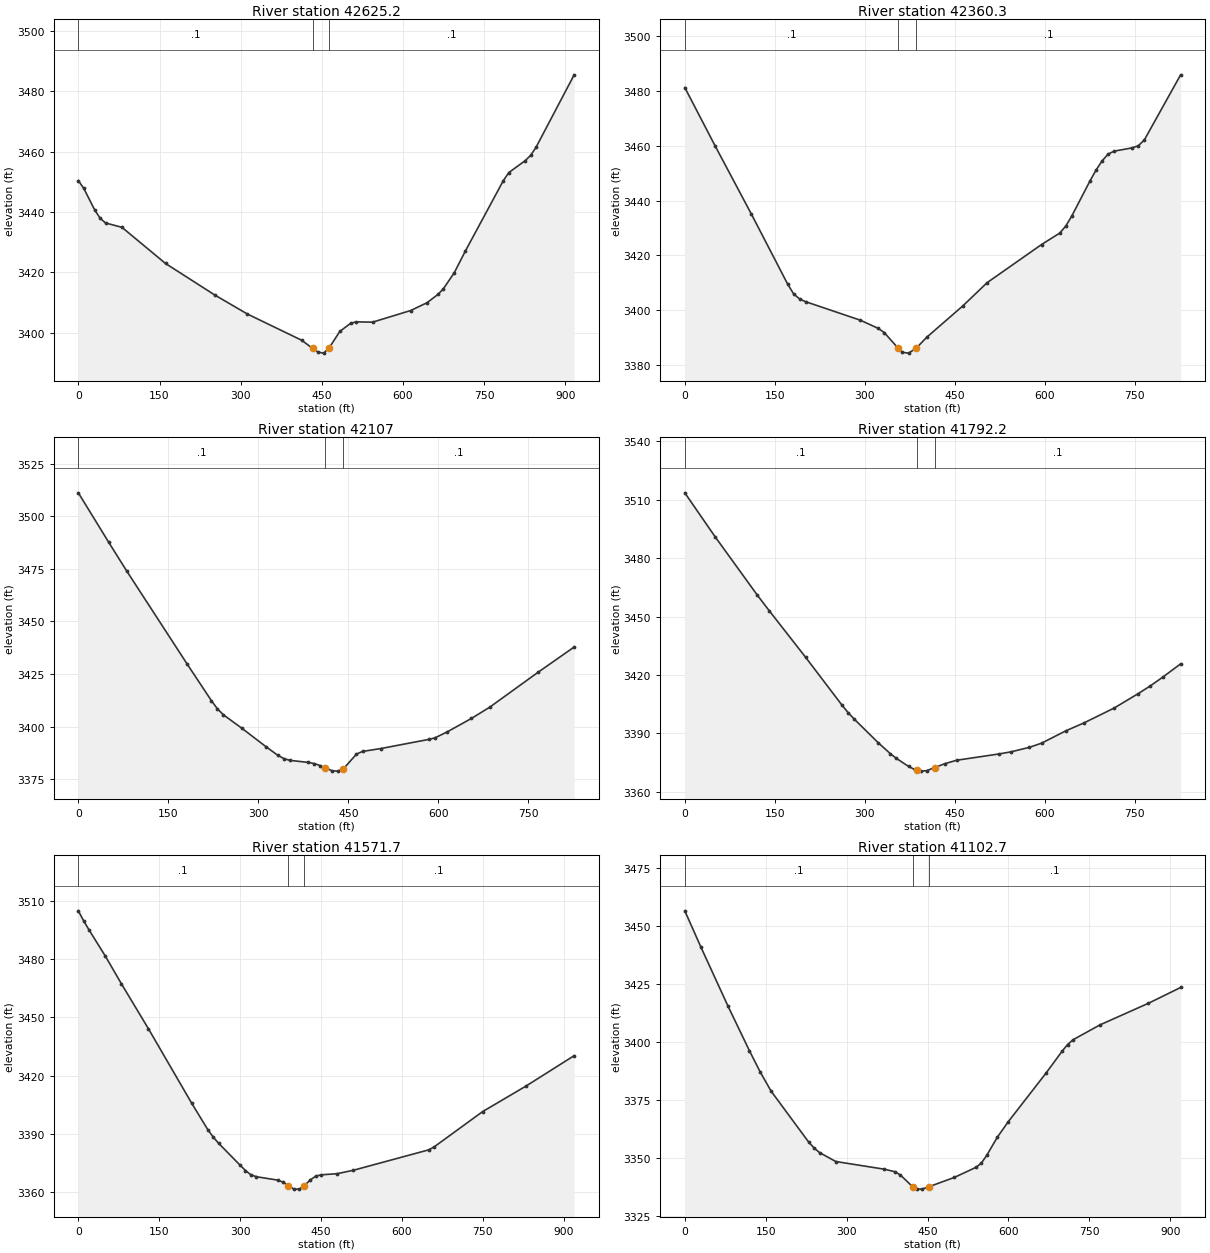
Type RM Length L Ch R = 1 ,42625.2 ,270.2,264.9,259.6
XS GIS Cut Line= 2
     2109791.706      394426.076     2110410.952      395101.349
#Sta/Elev= 30
       0 3450.45    10.1 3447.85    30.2 3440.74    40.3 3437.97    50.3 3436.41
    80.6 3434.96   161.1 3422.98   251.7 3412.57   312.1 3406.24   412.8 3397.51
   433.13394.795     443 3393.58   453.1 3393.25   463.1 3394.89   483.3 3400.48
   503.4 3403.16   513.5 3403.62   543.7 3403.52   614.2 3407.38   644.4 3409.97
   664.5 3412.71   674.6  3414.6   694.7 3419.91   714.8 3426.98   785.3 3450.43
   795.4 3453.11   825.6 3457.04   835.7  3458.8   845.7 3461.47   916.2 3485.52
#Mann= 3 , 0 , 0
       0      .1       0   433.1    .045       0   463.1      .1       0
Bank Sta=433.1,463.1
XS Rating Curve= 0 ,0
Exp/Cntr=0.3,0.1

Type RM Length L Ch R = 1 ,42360.3 ,246.5,253.3,260.2
XS GIS Cut Line= 2
     2109623.352      394756.905     2110308.701      395218.689
#Sta/Elev= 30
       0 3481.26    50.4 3460.02   110.9  3435.1   171.3 3409.57   181.4 3405.94
   191.5 3404.07   201.6 3403.08   292.3 3396.36   322.5 3393.35   332.6 3391.79
   355.63386.128   362.8 3384.61   372.9 3384.32   385.63386.085   403.1 3390.09
   463.6  3401.6   503.9 3410.04   594.6 3423.96   624.8 3428.12   634.9 3430.67
     645 3434.37   675.2 3447.12   685.3 3451.08   695.4 3454.46   705.5 3456.96
   715.6 3458.04   745.8 3459.25   755.9 3460.02   765.9 3462.13   826.4  3485.9
#Mann= 3 , 0 , 0
       0      .1       0   355.6    .045       0   385.6      .1       0
Bank Sta=355.6,385.6
XS Rating Curve= 0 ,0
Exp/Cntr=0.3,0.1

Type RM Length L Ch R = 1 ,42107   ,327.7,315,302.2
XS GIS Cut Line= 2
      2109510.79      394830.573      2110029.33      395474.051
#Sta/Elev= 30
       0 3511.07    50.4 3487.67    80.6 3473.93   181.4 3429.67   221.7 3412.33
   231.8  3408.4   241.9 3405.53   272.1 3399.27   312.4 3390.48   332.6 3386.29
   342.7 3384.73   352.7 3383.91     383 3382.94     393 3382.39   403.1 3381.45
   411.23380.351   423.3 3378.92   433.4 3378.79   441.23380.031   443.4 3380.38
   463.6 3386.89   473.7 3388.16   503.9 3389.51   584.5 3393.89   594.6 3394.63
   614.8 3397.44   655.1 3403.82   685.3 3409.11   765.9 3425.71   826.4 3437.78
#Mann= 3 , 0 , 0
       0      .1       0   411.2    .045       0   441.2      .1       0
Bank Sta=411.2,441.2
XS Rating Curve= 0 ,0
Exp/Cntr=0.3,0.1

Type RM Length L Ch R = 1 ,41792.2 ,216.4,220.3,224.2
XS GIS Cut Line= 2
     2109198.492      395206.919     2109968.245      395507.631
#Sta/Elev= 30
       0 3513.57    50.4 3491.06   120.9 3461.01   141.1 3452.86   201.6 3429.01
     262 3404.51   272.1 3400.71   282.2 3397.41   322.5 3385.17   342.7 3379.56
   352.7 3377.16   372.9 3373.05     383 3371.46   386.63371.158     393 3370.62
   403.1 3370.84   416.63372.468   433.4 3374.45   453.5 3376.23   524.1 3379.46
   544.2 3380.56   574.4 3382.85   594.6 3384.97   634.9  3391.3   665.2 3395.37
   715.6 3403.02   755.9 3410.46     776 3414.43   796.2  3418.8   826.4 3425.71
#Mann= 3 , 0 , 0
       0      .1       0   386.6    .045       0   416.6      .1       0
Bank Sta=386.6,416.6
XS Rating Curve= 0 ,0
Exp/Cntr=0.3,0.1

Type RM Length L Ch R = 1 ,41571.7 ,472.9,469,465.1
XS GIS Cut Line= 3
     2109140.527      395340.099     2109533.097       395579.46
     2109921.919      395824.206
#Sta/Elev= 30
       0 3505.14      10  3499.9      20 3495.21      50 3481.77      80 3467.36
   129.9 3444.21   209.9 3405.81   239.9 3392.08   249.9 3388.26   259.9 3385.02
   299.9 3373.66   309.9  3370.9   319.8 3368.72   329.8 3367.71   369.8 3365.93
   379.8 3364.85   388.73363.141   399.8 3361.28   409.8 3361.28   418.73363.024
   429.8    3366   439.8 3367.93   449.8 3368.66   479.8 3369.26   509.7 3371.02
   649.6 3381.58   659.5 3383.08   749.4 3401.34   829.3 3414.45   919.2 3430.27
#Mann= 3 , 0 , 0
       0      .1       0   388.7    .045       0   418.7      .1       0
Bank Sta=388.7,418.7
XS Rating Curve= 0 ,0
Exp/Cntr=0.3,0.1

Type RM Length L Ch R = 1 ,41102.7 ,276,275.8,275.9
XS GIS Cut Line= 3
     2108948.089      395797.999     2109374.693      395969.505
     2109798.486       396146.94
#Sta/Elev= 30
       0 3456.69      30 3440.96      80 3415.59   119.9 3396.25   139.9 3387.06
   159.9 3378.87   229.9 3356.77   239.9 3354.25   249.9  3352.3   279.9 3348.45
   369.8 3345.14   389.8 3344.04   399.8  3342.6   422.43337.574   429.8 3336.56
   439.8 3336.53   452.43337.552   499.7 3341.58   539.7 3345.93   549.7 3347.76
   559.7 3351.09   579.6 3359.02   599.6 3365.62   669.5 3386.58   699.5 3396.08
   709.5 3398.92   719.5 3400.99   769.4 3407.41   859.3 3416.75   919.2 3423.59
#Mann= 3 , 0 , 0
       0      .1       0   422.4    .045       0   452.4      .1       0
Bank Sta=422.4,452.4
XS Rating Curve= 0 ,0
Exp/Cntr=0.3,0.1

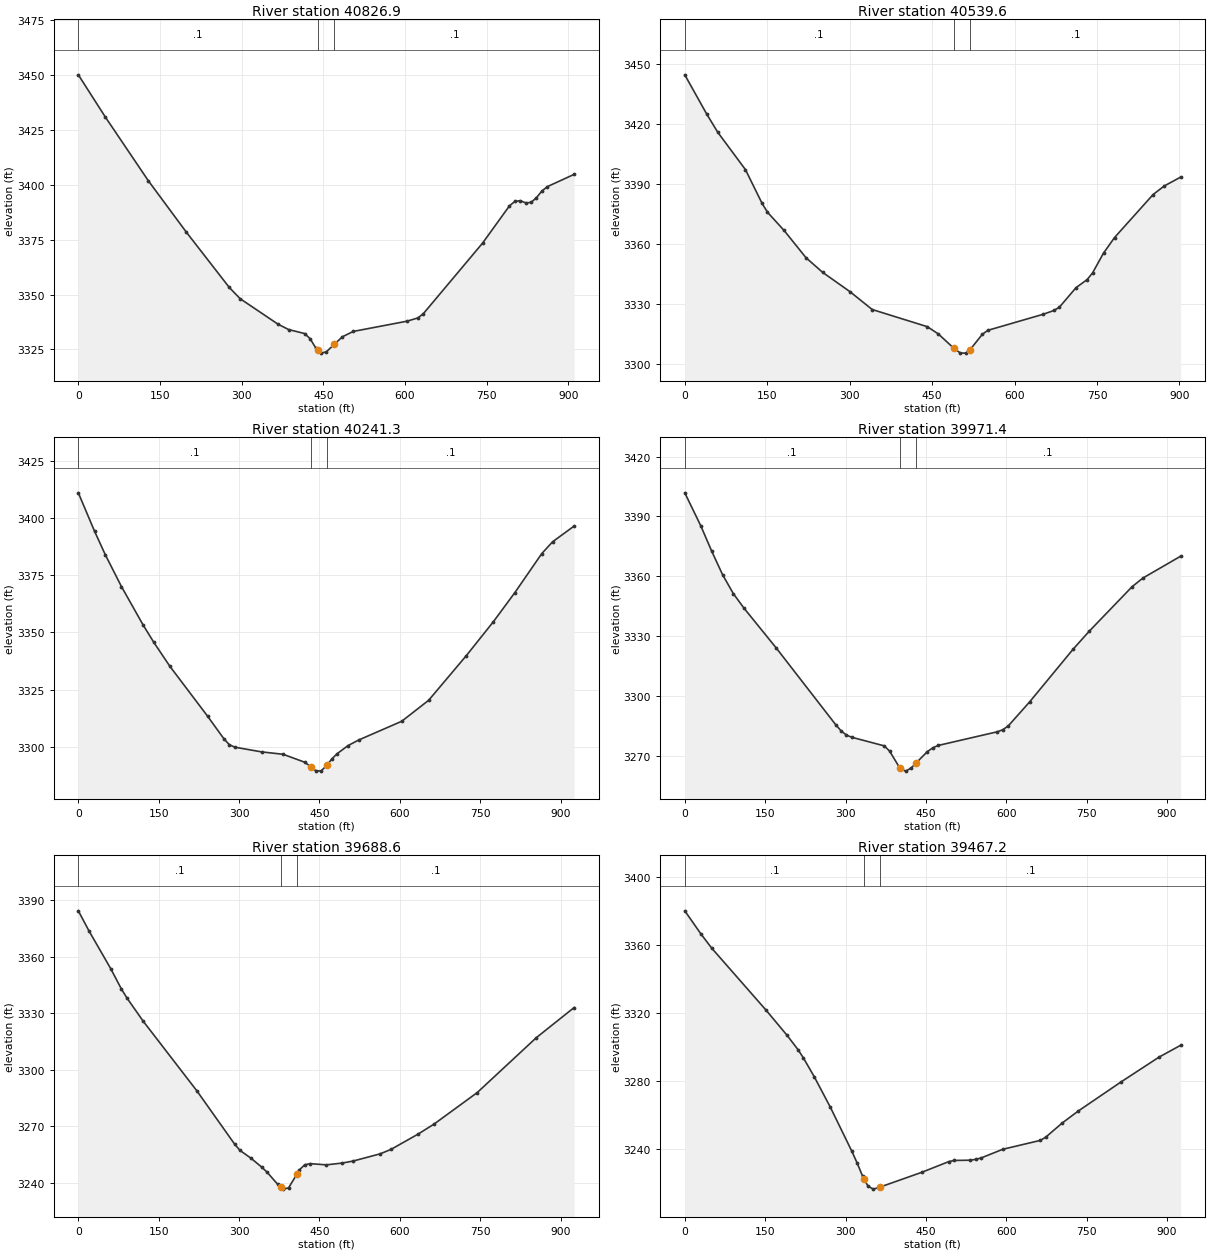
Type RM Length L Ch R = 1 ,40826.9 ,297,287.2,277.2
XS GIS Cut Line= 3
     2108845.928      396044.217     2109268.563      396214.128
     2109688.411      396389.911
#Sta/Elev= 30
       0 3450.01    49.5 3430.84   128.7 3401.75     198 3378.52   277.3 3353.21
   297.1 3348.13   366.4 3336.56   386.2 3334.06   415.9 3332.23   425.8 3329.87
   435.7 3325.84   440.53324.623   445.6 3323.33   455.5  3323.9   470.53327.433
   485.2  3330.8     505 3333.21   603.9 3337.88   623.7 3339.36   633.6 3341.26
   742.5 3373.41   791.9 3390.38   801.8 3392.39   811.7 3392.72   821.6 3391.75
   831.5  3391.9   841.4 3394.09   851.3 3397.06   861.2 3399.09   910.7 3404.71
#Mann= 3 , 0 , 0
       0      .1       0   440.5    .045       0   470.5      .1       0
Bank Sta=440.5,470.5
XS Rating Curve= 0 ,0
Exp/Cntr=0.3,0.1

Type RM Length L Ch R = 1 ,40539.6 ,300,298.4,296.7
XS GIS Cut Line= 3
     2108715.563       396524.55      2109165.89      396495.931
     2109616.228       396473.75
#Sta/Elev= 30
       0 3444.39    40.1 3424.68    60.2 3415.61   110.3 3397.06   140.4 3380.29
   150.4 3375.77   180.5  3366.7   220.6 3353.01   250.7 3345.75   300.8 3336.02
   340.9 3327.17   441.2 3318.59   461.2 3314.98   489.23307.888   501.3 3305.44
   511.4 3305.38   519.23307.159   541.4 3314.81   551.4 3316.77   651.6 3324.75
   671.7 3326.69   681.7 3328.38   711.8 3338.08   731.8 3342.06   741.8 3345.41
   761.8 3355.33   781.9 3363.13     852 3384.59   872.1 3388.84   902.1  3393.3
#Mann= 3 , 0 , 0
       0      .1       0   489.2    .045       0   519.2      .1       0
Bank Sta=489.2,519.2
XS Rating Curve= 0 ,0
Exp/Cntr=0.3,0.1

Type RM Length L Ch R = 1 ,40241.3 ,265.8,269.8,273.8
XS GIS Cut Line= 2
     2108807.604      396841.638     2109726.069        396729.1
#Sta/Elev= 30
       0 3411.16    30.2 3394.37    50.3 3384.06    80.5 3370.08   120.7 3353.35
   140.8 3345.68     171 3335.11   241.4 3313.25   271.6 3303.42   281.6 3300.86
   291.7 3299.74     342 3297.67   382.2 3296.62   422.4 3293.14   434.1 3291.13
   442.6 3289.49   452.6 3289.24   464.13291.857   472.7 3294.48   482.8 3296.84
   502.9 3300.37     523 3302.86   603.5 3311.08   653.8 3320.28   724.2 3339.88
   774.5 3354.68   814.7 3367.47     865 3384.58   885.1 3389.72   925.3 3396.62
#Mann= 3 , 0 , 0
       0      .1       0   434.1    .045       0   464.1      .1       0
Bank Sta=434.1,464.1
XS Rating Curve= 0 ,0
Exp/Cntr=0.3,0.1

Type RM Length L Ch R = 1 ,39971.4 ,280.8,282.7,284.7
XS GIS Cut Line= 2
     2108850.608      397030.622        2109775.      397072.372
#Sta/Elev= 30
       0 3401.86    30.2 3385.09    50.3 3372.53    70.4 3360.85    90.5 3351.31
   110.6 3343.95     171 3323.89   281.6 3285.53   291.7 3282.42   301.7  3280.3
   311.8 3279.21   372.2  3274.9   382.2 3272.29   400.93263.941   402.3 3263.34
   412.4 3262.23   422.4  3263.8   430.93266.122   452.6    3272   462.7  3273.9
   472.7  3275.1   583.4 3281.98   593.4    3283   603.5 3284.87   643.7 3297.02
   724.2 3323.26   754.4 3332.33   834.8 3354.78   854.9  3359.1   925.3 3370.06
#Mann= 3 , 0 , 0
       0      .1       0   400.9    .045       0   430.9      .1       0
Bank Sta=400.9,430.9
XS Rating Curve= 0 ,0
Exp/Cntr=0.3,0.1

Type RM Length L Ch R = 1 ,39688.6 ,224,221.5,219
XS GIS Cut Line= 2
     2108887.095      397256.955     2109803.339       397386.34
#Sta/Elev= 30
       0 3384.37    20.1 3373.59    60.4 3353.69    80.5 3342.78    90.5 3338.17
   120.7 3325.88   221.3 3288.72   291.7 3260.44   301.7 3257.11   321.9 3253.04
     342  3248.3     352 3245.62   372.2 3239.07   378.23237.558   382.2 3236.55
   392.3 3237.21   408.23244.636   412.4 3246.74   422.4 3249.45   432.5 3250.09
   462.7 3249.44   492.8 3250.41     513 3251.48   563.2 3255.29   583.4 3257.64
   633.6  3265.7   663.8 3271.09   744.3 3287.81   854.9 3317.05   925.3 3333.01
#Mann= 3 , 0 , 0
       0      .1       0   378.2    .045       0   408.2      .1       0
Bank Sta=378.2,408.2
XS Rating Curve= 0 ,0
Exp/Cntr=0.3,0.1

Type RM Length L Ch R = 1 ,39467.2 ,292.6,291.6,290.5
XS GIS Cut Line= 2
     2108860.017      397510.375     2109784.945      397537.786
#Sta/Elev= 30
       0 3380.28    30.2 3366.64    50.3 3358.32   150.9 3322.17   191.1 3307.01
   211.2 3298.72   221.3 3293.84   241.4 3282.87   271.6 3264.86   311.8 3238.91
   321.9 3231.85   331.9 3224.22   335.1 3222.36     342 3218.35     352 3216.69
   365.13217.986   442.6 3226.62   492.8 3232.89   502.9 3233.55   533.1  3233.7
   543.1  3234.2   553.2 3235.04   593.4 3240.11   663.8 3245.37   673.9 3247.33
   704.1 3255.49   734.2 3262.59   814.7 3279.83   885.1 3294.31   925.3 3301.24
#Mann= 3 , 0 , 0
       0      .1       0   335.1    .045       0   365.1      .1       0
Bank Sta=335.1,365.1
XS Rating Curve= 0 ,0
Exp/Cntr=0.3,0.1

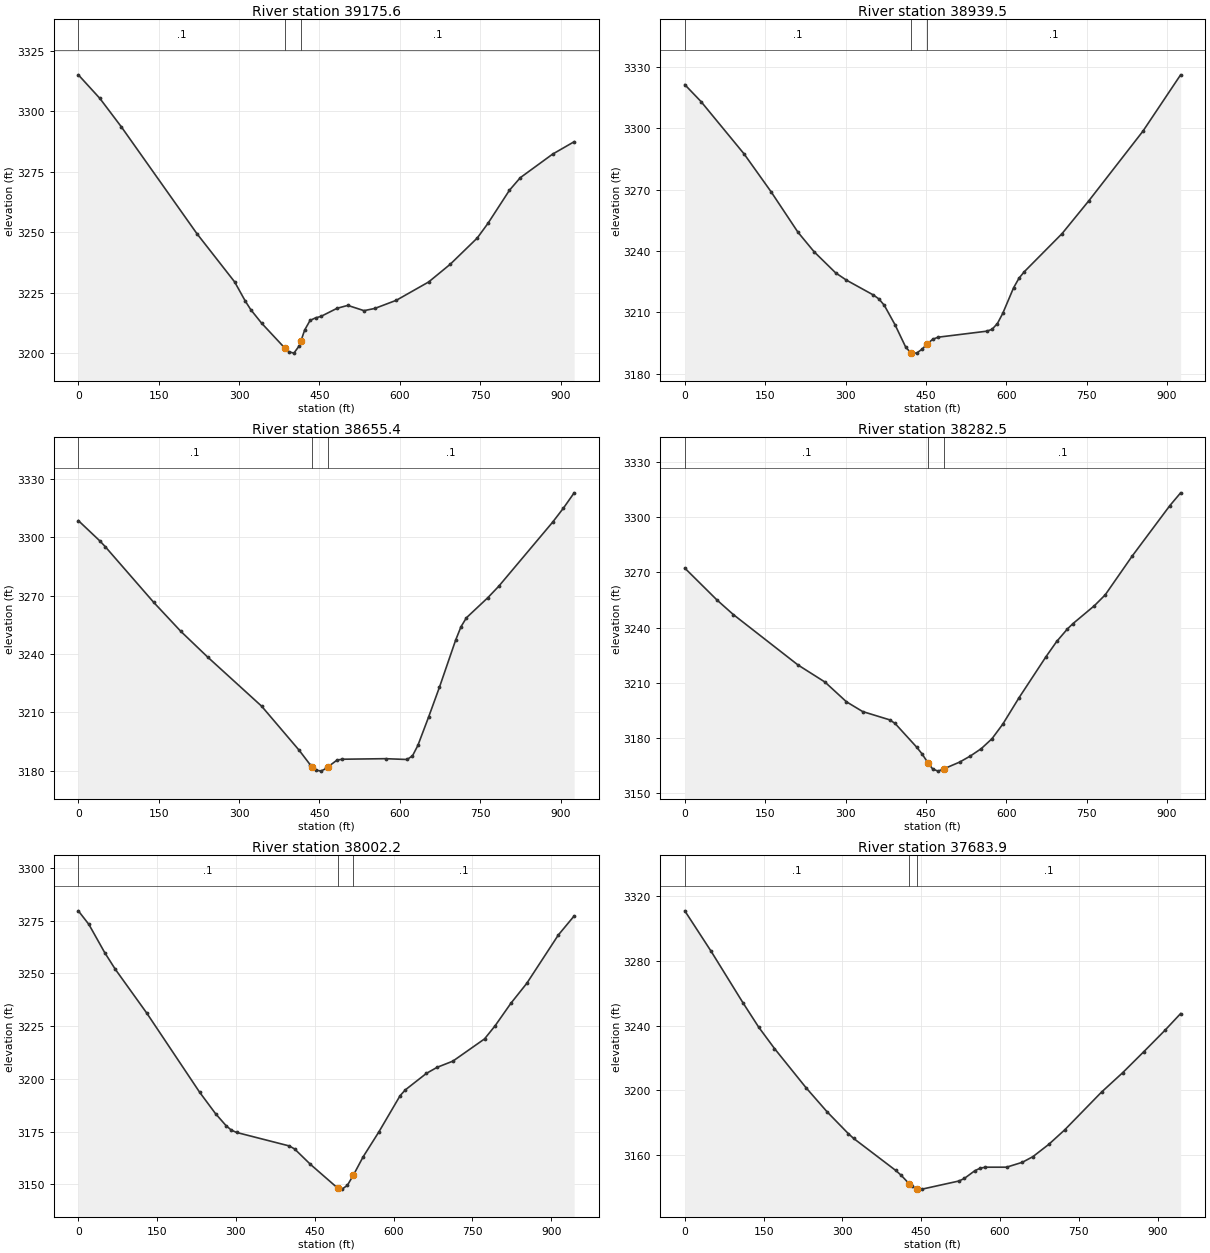
Type RM Length L Ch R = 1 ,39175.6 ,226.5,236.1,245.6
XS GIS Cut Line= 2
     2108896.216      397803.004     2109821.392      397785.912
#Sta/Elev= 30
       0 3315.17    40.2 3305.41    80.5 3293.57   221.3 3249.43   291.7 3229.46
   311.8 3221.44   321.9 3217.94     342 3212.39   385.43202.052   392.3 3200.59
   402.3 3199.98   412.4 3203.06   415.43205.007   422.4 3209.55   432.5 3213.53
   442.6 3214.57   452.6 3215.16   482.8 3218.53   502.9 3219.74   533.1 3217.56
   553.2 3218.47   593.4 3221.85   653.8 3229.44     694 3236.76   744.3 3247.59
   764.4 3253.68   804.6 3267.42   824.8  3272.6   885.1 3282.35   925.3 3287.48
#Mann= 3 , 0 , 0
       0      .1       0   385.4    .045       0   415.4      .1       0
Bank Sta=385.4,415.4
XS Rating Curve= 0 ,0
Exp/Cntr=0.3,0.1

Type RM Length L Ch R = 1 ,38939.5 ,284.1,284.2,284.2
XS GIS Cut Line= 2
     2108828.385       397839.25     2109681.511      398197.606
#Sta/Elev= 30
       0 3321.31    30.2 3313.06   110.6 3287.48   160.9 3269.02   211.2  3249.2
   241.4 3239.64   281.6 3229.33   301.7 3225.79     352 3218.53   362.1 3216.64
   372.2 3213.55   392.3 3204.02   412.4    3193     4223190.273   432.5 3190.14
   442.6 3192.02     4523194.558   462.7 3196.91   472.7 3197.92   563.2 3200.85
   573.3 3201.75   583.4  3204.6   593.4 3209.59   613.5 3222.02   623.6 3226.72
   633.6 3229.92   704.1 3248.55   754.4  3264.7   854.9 3298.56   925.3  3326.1
#Mann= 3 , 0 , 0
       0      .1       0     422    .045       0     452      .1       0
Bank Sta=422,452
XS Rating Curve= 0 ,0
Exp/Cntr=0.3,0.1

Type RM Length L Ch R = 1 ,38655.4 ,367.2,372.8,378.4
XS GIS Cut Line= 2
      2108695.37      398089.021     2109548.497      398447.376
#Sta/Elev= 30
       0 3308.66    40.2 3298.19    50.3 3295.22   140.8 3266.56   191.1 3251.74
   241.4 3238.46     342 3213.23   412.4 3190.44   432.5 3183.17   436.33182.139
   442.6 3180.43   452.6 3179.81   462.7 3181.23   466.33182.101   482.8 3185.49
   492.8 3185.93   573.3 3186.21   613.5 3185.79   623.6 3187.68   633.6    3193
   653.8 3207.72   673.9 3222.96   704.1 3247.16   714.1 3254.06   724.2 3258.66
   764.4 3269.06   784.5 3274.86   885.1 3307.83   905.2 3315.04   925.3 3322.93
#Mann= 3 , 0 , 0
       0      .1       0   436.3    .045       0   466.3      .1       0
Bank Sta=436.3,466.3
XS Rating Curve= 0 ,0
Exp/Cntr=0.3,0.1

Type RM Length L Ch R = 1 ,38282.5 ,281.8,280.3,278.9
XS GIS Cut Line= 2
     2108638.065      398338.023     2109379.687      398891.412
#Sta/Elev= 30
       0 3272.35    60.4 3254.94    90.5 3247.14   211.2 3219.76   261.5 3210.49
   301.7 3199.75   331.9 3194.46   382.2 3189.97   392.3 3188.03   432.5  3175.2
   442.6 3171.52   453.73166.663   462.7 3163.25   472.7 3162.11   483.73163.377
     513 3167.03   533.1 3170.36   553.2  3174.3   573.3 3179.72   593.4 3187.61
   623.6  3201.9   673.9 3224.18     694  3232.5   714.1 3239.33   724.2 3242.16
   764.4 3251.94   784.5  3257.8   834.8 3278.84   905.2 3306.28   925.3 3313.22
#Mann= 3 , 0 , 0
       0      .1       0   453.7    .045       0   483.7      .1       0
Bank Sta=453.7,483.7
XS Rating Curve= 0 ,0
Exp/Cntr=0.3,0.1

Type RM Length L Ch R = 1 ,38002.2 ,326.1,318.3,310.2
XS GIS Cut Line= 2
      2108461.52      398584.507     2109250.598      399102.402
#Sta/Elev= 30
       0 3279.68    20.1 3273.24    50.2 3259.88    70.3 3252.01   130.5 3231.13
   230.9 3193.71   261.1 3183.58   281.2 3177.87   291.2 3175.76   301.2 3174.65
   401.6 3168.25   411.7 3166.82   441.8 3159.53   493.63148.293     502 3147.79
   512.1 3149.58   523.63154.456   542.2 3163.14   572.3    3175   612.5 3192.08
   622.5 3194.84   662.7 3202.67   682.8  3205.5   712.9 3208.44   773.2 3218.98
   793.2 3225.16   823.4 3235.88   853.5 3245.28   913.7 3268.24   943.8 3277.26
#Mann= 3 , 0 , 0
       0      .1       0   493.6    .045       0   523.6      .1       0
Bank Sta=493.6,523.6
XS Rating Curve= 0 ,0
Exp/Cntr=0.3,0.1

Type RM Length L Ch R = 1 ,37683.9 ,186.8,181.1,175.6
XS GIS Cut Line= 2
     2108220.912      398963.107     2109138.719       399183.31
#Sta/Elev= 30
       0 3310.72    50.2 3285.71   110.4 3254.18   140.6 3239.01   170.7 3225.81
   230.9 3201.58   271.1 3186.68   311.3 3173.31   321.3 3170.38   401.6 3150.59
   411.7 3147.69   427.1 3142.38   431.8 3140.86   442.1 3139.21   451.8 3139.09
   522.1 3144.12   532.2  3145.7   552.2 3150.47   562.3    3152   572.3 3152.62
   612.5 3152.62   642.6 3155.65   662.7 3159.14   692.8 3166.69     723 3175.59
   793.2 3198.92   833.4 3210.87   873.6 3223.81   913.7 3236.95   943.8 3247.36
#Mann= 3 , 0 , 0
       0      .1       0   427.1    .045       0   442.1      .1       0
Bank Sta=427.1,442.1
XS Rating Curve= 0 ,0
Exp/Cntr=0.3,0.1

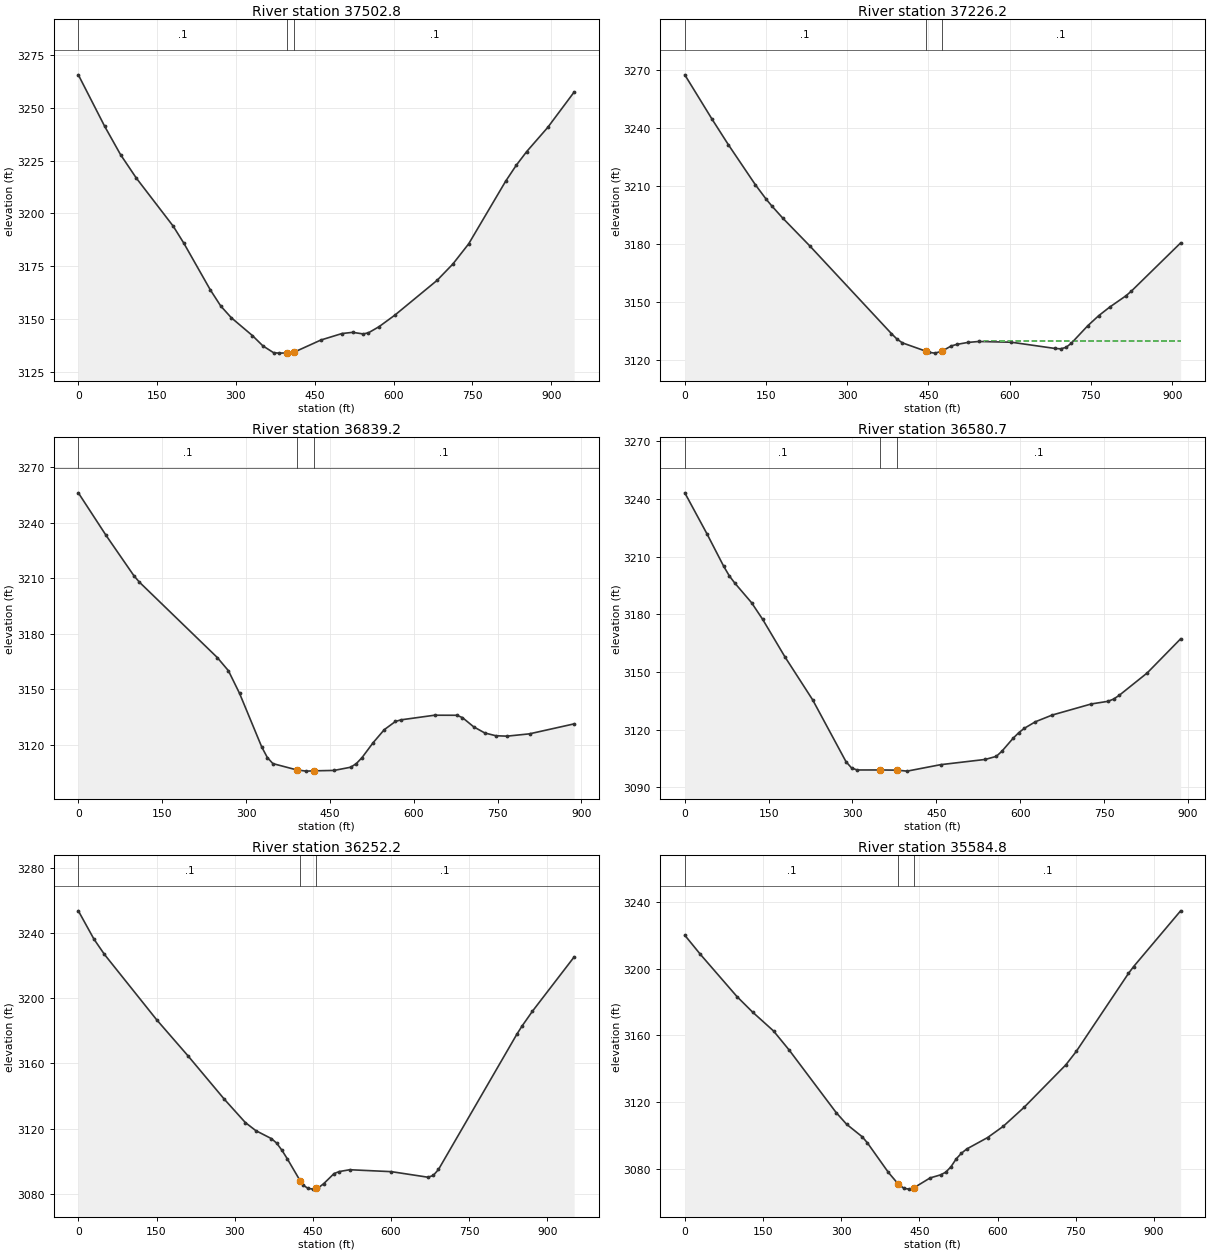
Type RM Length L Ch R = 1 ,37502.8 ,265.1,276.6,289.1
XS GIS Cut Line= 2
     2108227.261      399245.246     2109170.981       399229.37
#Sta/Elev= 30
       0 3265.71    50.2 3241.28    80.3  3227.9   110.4 3216.75   180.7 3193.93
   200.8  3185.9     251 3163.87   271.1 3156.11   291.2 3150.56   331.4 3142.09
   351.4  3137.2   371.5 3134.01   381.6 3133.78   396.3 3133.87   411.3  3134.3
   461.9 3140.01     502 3143.08   522.1 3143.63   542.2 3142.88   552.2 3143.41
   572.3  3146.3   602.5 3151.79   682.8 3168.26   712.9 3176.02     743 3185.58
   813.3 3215.24   833.4 3222.77   853.5 3229.34   893.6 3240.81   943.8 3257.56
#Mann= 3 , 0 , 0
       0      .1       0   396.3    .045       0   411.3      .1       0
Bank Sta=396.3,411.3
XS Rating Curve= 0 ,0
Exp/Cntr=0.3,0.1

Type RM Length L Ch R = 1 ,37226.2 ,385.7,387,387.4
XS GIS Cut Line= 3
     2108210.269      399291.744     2108617.118      399510.247
     2109006.259      399743.702
#Sta/Elev= 30
       0 3267.46    50.2 3244.55    80.3 3231.34   130.5 3210.46   150.6 3202.94
   160.6 3199.59   180.7 3193.32   230.9 3178.84   381.5 3133.47   391.5 3130.71
   401.6 3128.68   444.63124.394   451.8 3123.71   461.8 3123.34   474.63124.313
   492.1 3127.07   502.2 3127.85   522.3 3128.86   542.5 3129.37     603 3128.99
   683.7 3125.76   693.8 3125.58   703.8 3126.28   713.9  3128.5   744.2 3137.55
   764.3 3142.73   784.5 3147.15   814.8 3153.06   824.8 3155.49   915.6 3180.41
#Mann= 3 , 0 , 0
       0      .1       0   444.6    .045       0   474.6      .1       0
#XS Ineff= 2 , 0
                          552.65         3129.41
Permanent Ineff=
       F       F
Bank Sta=444.6,474.6
XS Rating Curve= 0 ,0
Exp/Cntr=0.3,0.1

Type RM Length L Ch R = 1 ,36839.2 ,254.6,258.5,262.4
XS GIS Cut Line= 3
     2108107.163      399646.034       2108488.1      399880.967
     2108850.837        400129.2
#Sta/Elev= 30
       0 3256.24    49.7  3233.2    99.5  3211.4   109.4 3207.92   248.6 3167.21
   268.5 3160.08   288.4 3147.86   328.2 3118.81   338.2 3113.12   348.1 3109.86
   390.83106.448   407.8 3105.79   420.83105.939   457.6 3106.17   487.5 3107.92
   497.5 3109.91   507.5 3113.08   527.5 3121.19   547.4 3128.21   567.4 3132.65
   577.4 3133.52   637.4 3136.02   677.3 3135.99   687.3 3134.71   707.3 3129.75
   727.3  3126.4   747.2 3124.91   767.2  3124.7   807.2 3125.95   887.1 3131.34
#Mann= 3 , 0 , 0
       0      .1       0   390.8    .045       0   420.8      .1       0
Bank Sta=390.8,420.8
XS Rating Curve= 0 ,0
Exp/Cntr=0.3,0.1

Type RM Length L Ch R = 1 ,36580.7 ,326.4,328.5,330.6
XS GIS Cut Line= 3
      2108004.48      399808.143     2108340.446      400103.835
     2108656.233      400409.574
#Sta/Elev= 30
       0 3243.14    39.8 3221.75    69.6 3204.96    79.6    3200    89.5 3196.21
   119.4 3186.05   139.2 3177.42     179 3157.94   228.8 3135.51   288.4 3103.39
   298.4  3100.1   308.3 3099.07   349.83099.074   379.83098.979   397.8 3098.47
   457.6 3101.82   537.5 3104.55   557.4 3106.15   567.4 3108.84   587.4 3115.55
   597.4 3118.42   607.4 3120.72   627.4 3124.15   657.3 3127.62   727.3 3133.39
   757.2 3134.76   767.2 3135.93   777.2 3137.86   827.2 3149.48   887.1 3167.24
#Mann= 3 , 0 , 0
       0      .1       0   349.8    .045       0   379.8      .1       0
Bank Sta=349.8,379.8
XS Rating Curve= 0 ,0
Exp/Cntr=0.3,0.1

Type RM Length L Ch R = 1 ,36252.2 ,666.9,667.4,667.9
XS GIS Cut Line= 2
     2107767.903      399975.881      2108425.11      400663.721
#Sta/Elev= 30
       0 3253.62      30 3236.25    50.1 3226.89   150.2 3186.83   210.3 3164.71
   280.4 3137.95   320.4 3123.76   340.5  3118.8   370.5 3113.88   380.5 3111.14
   390.6 3106.76   400.6 3101.69     4263087.818   430.6 3085.55   440.6 3083.36
   450.6 3082.91     4563083.364   460.6 3083.75   470.7 3086.24   490.7 3092.47
   500.7 3093.69   520.7 3094.81   600.8 3093.62   670.9 3090.21     681  3091.3
     691 3094.96   841.2 3177.84   851.2 3182.89   871.2 3192.01   951.3 3225.34
#Mann= 3 , 0 , 0
       0      .1       0     426    .045       0     456      .1       0
Bank Sta=426,456
XS Rating Curve= 0 ,0
Exp/Cntr=0.3,0.1

Type RM Length L Ch R = 1 ,35584.8 ,476.1,475.1,466.7
XS GIS Cut Line= 2
     2107353.426      400317.863     2108010.632      401005.704
#Sta/Elev= 30
       0 3220.13      30 3208.62   100.1 3183.31   130.2 3173.96   170.2 3162.69
   200.3 3151.19   290.4 3113.68   310.4 3106.68   340.5 3099.12   350.5 3095.43
   390.6 3077.76   409.63070.741   420.6 3068.17   430.6 3067.72   439.63068.521
   470.7 3074.45   490.7 3076.28   500.7 3077.89   510.7 3081.15   520.7 3085.88
   530.8 3089.28   540.8 3091.79   580.8 3098.65   610.9  3105.4   650.9  3116.8
     731  3142.3   751.1  3150.4   851.2  3197.2   861.2 3201.35   951.3 3234.78
#Mann= 3 , 0 , 0
       0      .1       0   409.6    .045       0   439.6      .1       0
Bank Sta=409.6,439.6
XS Rating Curve= 0 ,0
Exp/Cntr=0.3,0.1

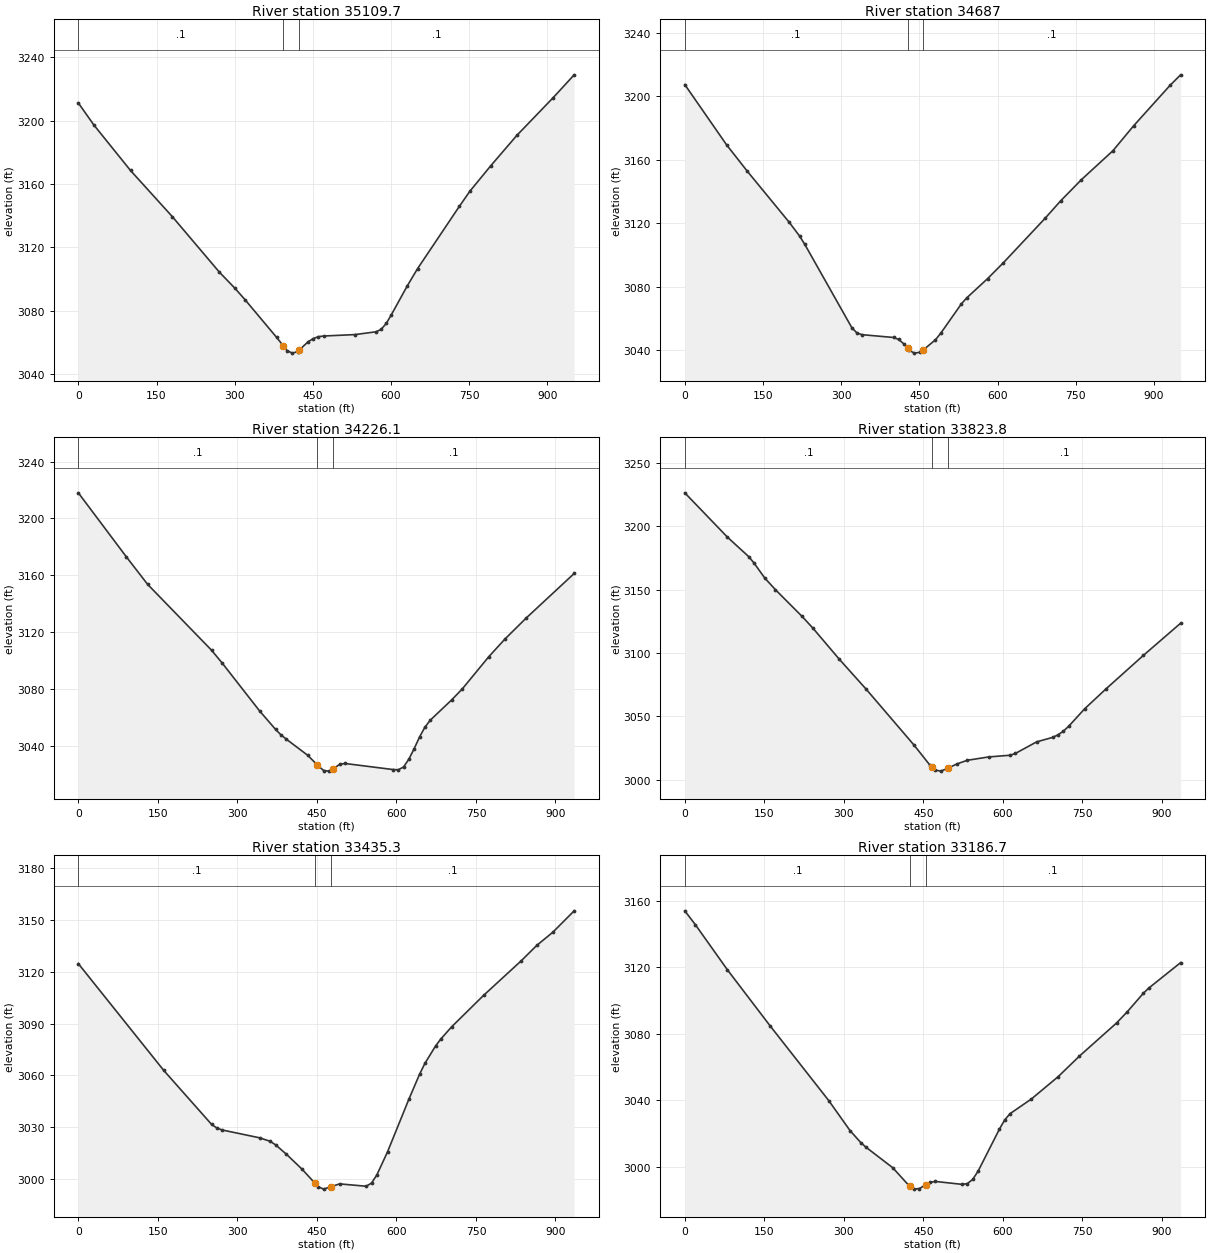
Type RM Length L Ch R = 1 ,35109.7 ,423.4,422.6,429.3
XS GIS Cut Line= 2
     2107062.728      400597.527     2107719.935      401285.368
#Sta/Elev= 30
       0 3211.25      30 3197.26   100.1 3168.59   180.2 3139.48   270.4 3104.43
   300.4  3094.2   320.4 3086.73   380.5  3063.1   393.23057.824   400.6 3054.76
   410.6 3053.19   420.6 3054.14   423.23054.972   440.6 3060.28   450.6 3062.37
   460.6 3063.59   470.7 3064.01   530.8  3064.9   570.8 3066.66   580.8 3068.13
   590.8 3071.97   600.8 3077.57   630.9 3095.56   650.9  3106.6     731 3145.91
   751.1 3155.43   791.1 3171.49   841.2 3190.71   911.3 3214.68   951.3 3229.02
#Mann= 3 , 0 , 0
       0      .1       0   393.2    .045       0   423.2      .1       0
Bank Sta=393.2,423.2
XS Rating Curve= 0 ,0
Exp/Cntr=0.3,0.1

Type RM Length L Ch R = 1 ,34687   ,457.9,461,464
XS GIS Cut Line= 2
     2106779.423      400858.044      2107436.63      401545.884
#Sta/Elev= 30
       0 3207.35    80.1 3169.47   120.2  3152.7   200.3  3120.7   220.3 3111.98
   230.3 3106.73   320.4 3054.38   330.5 3050.93   340.5 3049.92   400.6 3048.17
   410.6  3046.9   420.6 3044.04   427.53041.308   430.6 3040.08   440.6 3038.32
   450.6 3038.84   457.53040.317   480.7 3046.66   490.7 3050.68   530.8 3069.39
   540.8 3073.07   580.8 3085.17   610.9  3095.1     691 3123.09     721 3134.13
   761.1 3147.56   821.2 3165.65   861.2 3181.44   931.3 3206.98   951.3  3213.5
#Mann= 3 , 0 , 0
       0      .1       0   427.5    .045       0   457.5      .1       0
Bank Sta=427.5,457.5
XS Rating Curve= 0 ,0
Exp/Cntr=0.3,0.1

Type RM Length L Ch R = 1 ,34226.1 ,405.6,402.3,399
XS GIS Cut Line= 2
     2106471.242      401114.097     2107023.854      401868.583
#Sta/Elev= 30
       0 3217.99    90.5 3173.03   130.7 3153.66   251.4 3107.31   271.5 3098.27
   341.9 3064.69   372.1 3051.68   382.1 3047.94   392.2 3044.87   432.4 3033.58
   450.33026.914   462.6 3022.81   472.6 3022.38   480.33023.897   492.8  3027.1
   502.8 3027.76   593.3  3023.5   603.4 3023.32   613.4 3025.28   623.5 3030.84
   633.5 3038.22   643.6 3046.37   653.6 3053.21   663.7 3058.16   703.9 3072.36
     724 3080.08   774.3 3102.86   804.5 3115.16   844.7 3129.98   935.2 3161.29
#Mann= 3 , 0 , 0
       0      .1       0   450.3    .045       0   480.3      .1       0
#XS Ineff= 2 , 0
                          503.99         3027.63
Permanent Ineff=
       F       F
Bank Sta=450.3,480.3
XS Rating Curve= 0 ,0
Exp/Cntr=0.3,0.1

Type RM Length L Ch R = 1 ,33823.8 ,380.3,388.4,396.5
XS GIS Cut Line= 2
     2106072.801      401361.839     2106727.887       402029.29
#Sta/Elev= 30
       0  3226.4    80.4 3191.45   120.7 3176.02   130.7 3170.96   150.8  3159.2
     171 3149.99   221.2 3128.93   241.4 3119.79   291.6 3095.07   341.9 3071.62
   432.4 3027.43   462.6 3011.48   466.93009.868   472.6 3007.73   482.7  3006.9
   496.93009.281   512.9 3012.54     533 3015.47   573.2 3018.09   613.4 3019.43
   623.5 3020.84   663.7 3029.99   693.9 3033.52   703.9 3035.53     714 3038.41
     724 3042.25   754.2 3056.07   794.4 3071.75   864.8 3098.13   935.2 3123.57
#Mann= 3 , 0 , 0
       0      .1       0   466.9    .045       0   496.9      .1       0
Bank Sta=466.9,496.9
XS Rating Curve= 0 ,0
Exp/Cntr=0.3,0.1

Type RM Length L Ch R = 1 ,33435.3 ,248.7,249.2,249.6
XS GIS Cut Line= 2
     2106056.914       401620.01     2106444.492      402471.135
#Sta/Elev= 30
       0 3124.75   160.9 3062.99   251.4 3031.64   261.5 3029.51   271.5 3028.41
   341.9 3023.89     362 3021.85   372.1  3019.8   392.2 3014.47   422.4 3005.59
   446.2 2997.62   452.5 2995.56   462.6 2994.17   476.22995.535   492.8 2997.21
     543 2995.84   553.1 2997.72   563.1 3002.43   583.2 3015.77   623.5 3046.27
   643.6 3060.68   653.6 3066.96   673.8 3077.08   683.8 3081.15   703.9  3088.1
   764.3 3106.36   834.7 3126.21   864.8 3135.35     895 3142.96   935.2 3155.34
#Mann= 3 , 0 , 0
       0      .1       0   446.2    .045       0   476.2      .1       0
Bank Sta=446.2,476.2
XS Rating Curve= 0 ,0
Exp/Cntr=0.3,0.1

Type RM Length L Ch R = 1 ,33186.7 ,216.7,210.6,204.5
XS GIS Cut Line= 2
     2105838.072       401712.95      2106225.65      402564.074
#Sta/Elev= 30
       0 3153.87    20.1 3145.47    80.4 3118.43   160.9 3084.78   271.5 3039.89
   311.7 3021.86   331.8  3014.7   341.9 3011.84   392.2 2999.56   424.32988.328
   432.4  2986.7   442.5 2987.07   454.32989.248   462.6 2990.76   472.6 2991.32
   522.9 2989.57     533 2990.01     543 2992.54   553.1 2997.42   593.3 3022.67
   603.4 3028.27   613.4 3032.01   653.6 3040.81   703.9 3054.16   744.2 3066.57
   814.5 3086.54   834.7 3093.28   864.8 3104.32   874.9 3107.42   935.2 3122.76
#Mann= 3 , 0 , 0
       0      .1       0   424.3    .045       0   454.3      .1       0
Bank Sta=424.3,454.3
XS Rating Curve= 0 ,0
Exp/Cntr=0.3,0.1