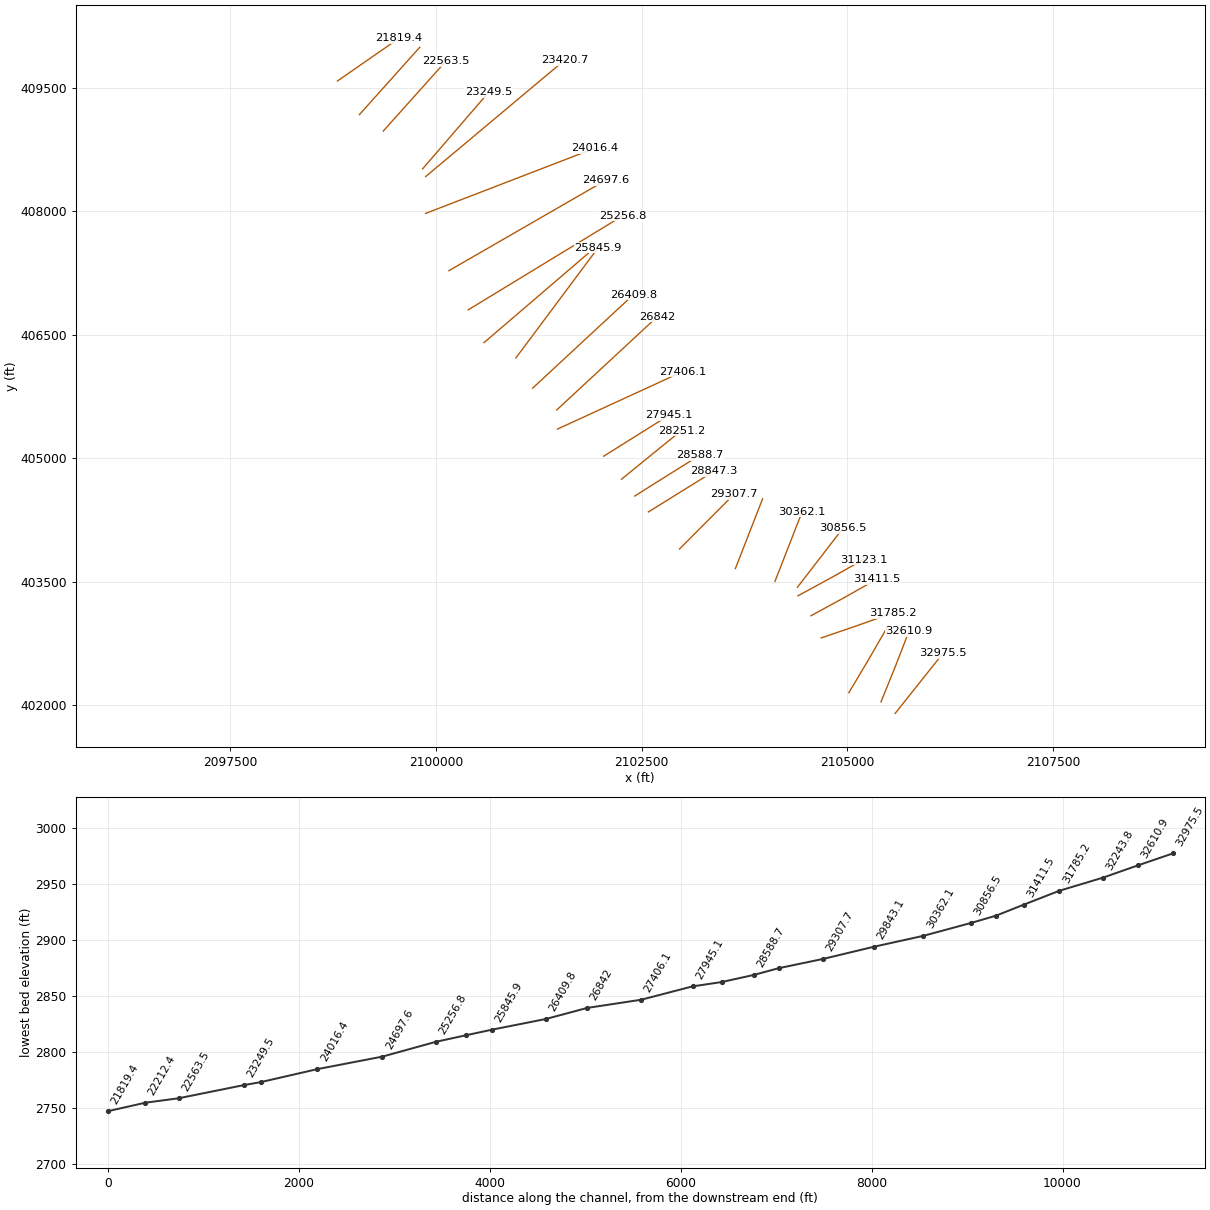
HEC-RAS study LaurCk.prj: LaurCk

--- LaurCk.g01 (geometry) --- (continued)

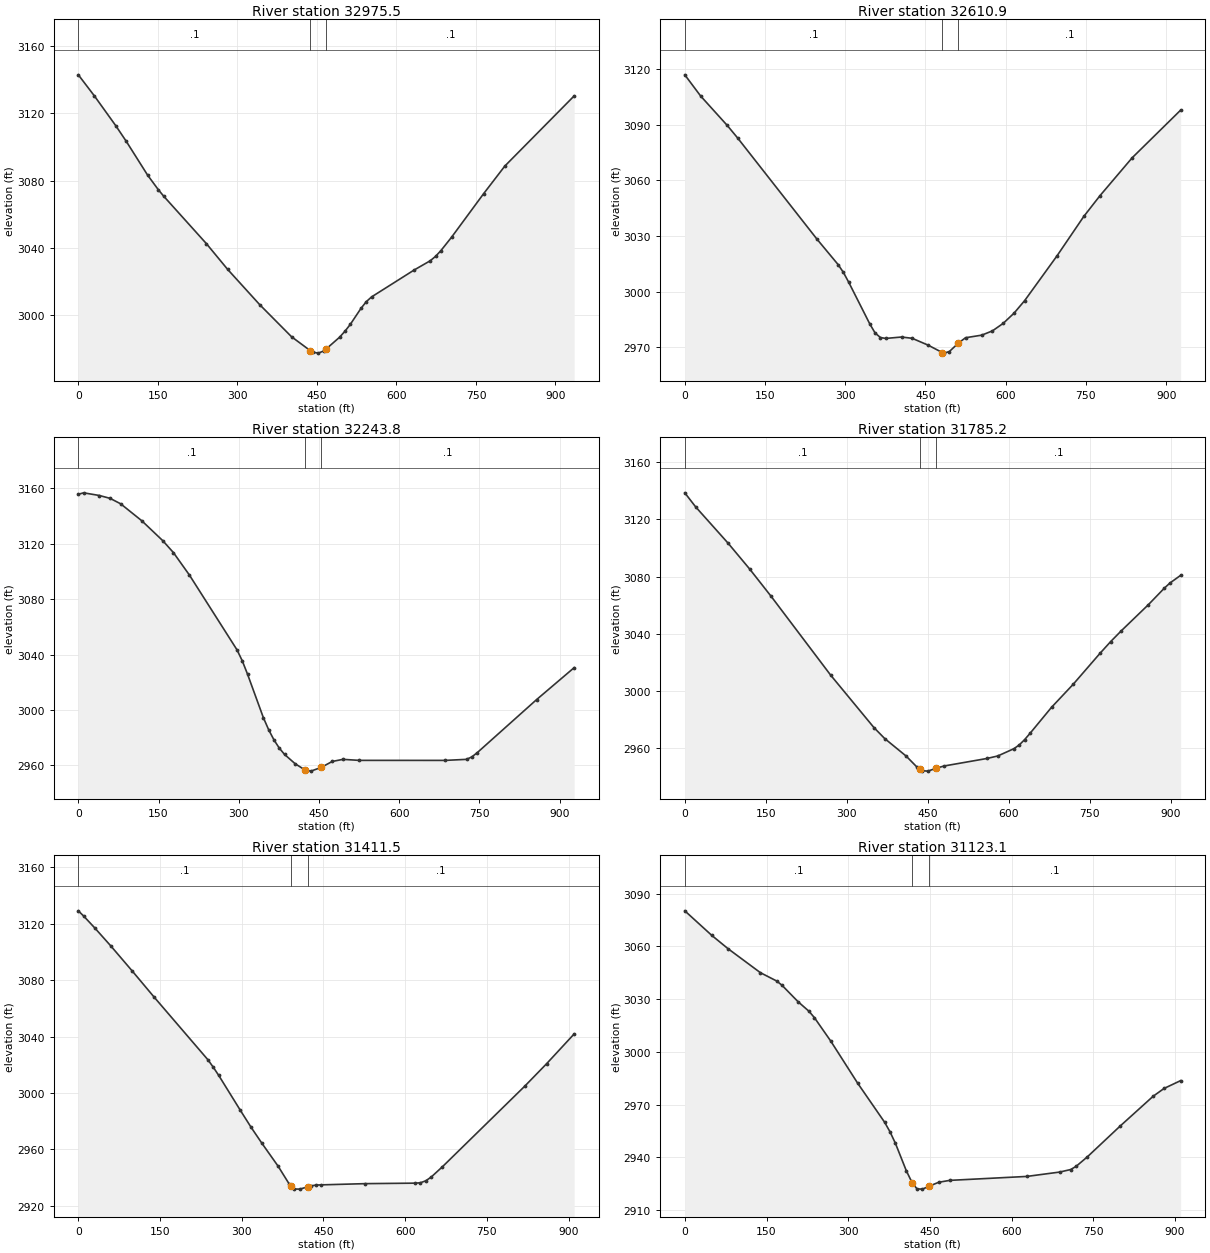
Type RM Length L Ch R = 1 ,32975.5 ,357.7,364.6,371.4
XS GIS Cut Line= 2
     2105583.424      401900.453     2106165.996      402632.053
#Sta/Elev= 30
       0 3142.72    30.2 3130.25    70.4 3112.63    90.5 3103.22   130.7 3083.19
   150.8  3074.6   160.9 3070.75   241.4 3042.61   281.6  3027.3   341.9 3006.42
   402.2  2987.3   437.82979.007   442.5 2978.16   452.5  2977.6   462.6 2978.84
   467.82980.161   492.8 2987.05   502.8 2990.57   512.9 2994.62     533  3004.1
     543 3008.09   553.1 3010.96   633.5 3026.94   663.7 3032.39   673.8 3035.02
   683.8  3038.4   703.9 3046.34   764.3 3072.15   804.5 3088.61   935.2 3130.21
#Mann= 3 , 0 , 0
       0      .1       0   437.8    .045       0   467.8      .1       0
Bank Sta=437.8,467.8
XS Rating Curve= 0 ,0
Exp/Cntr=0.3,0.1

Type RM Length L Ch R = 1 ,32610.9 ,372.8,367.2,357.8
XS GIS Cut Line= 3
     2105410.542       402038.93     2105584.943      402469.501
     2105752.542      402900.507
#Sta/Elev= 30
       0  3116.8    29.6  3105.4    79.1 3089.64    98.8 3082.79   247.1 3028.33
   286.6 3014.64   296.5 3010.42   306.4 3005.15   345.9 2982.65   355.8  2977.8
   365.7 2975.36   375.6 2974.86   405.2 2975.62     425 2974.94   454.7 2971.28
   481.42967.273   484.7 2966.95   494.7 2967.81   511.42972.344   524.9 2975.24
     555 2976.62   575.1 2978.92   595.2 2982.96   615.4 2988.42   635.4 2995.22
   695.8 3019.29     746 3040.57   776.2 3051.72   836.5 3072.16     927 3097.78
#Mann= 3 , 0 , 0
       0      .1       0   481.4    .045       0   511.4      .1       0
Bank Sta=481.4,511.4
XS Rating Curve= 0 ,0
Exp/Cntr=0.3,0.1

Type RM Length L Ch R = 1 ,32243.8 ,475.6,458.6,441.8
XS GIS Cut Line= 3
     2105020.092      402151.454     2105257.994      402550.465
      2105489.24      402950.941
#Sta/Elev= 30
       0 3155.61     9.9 3156.66    39.5 3154.73    59.3 3152.68    79.1 3148.75
   118.6 3136.53   158.1 3122.06   177.9  3113.5   207.6  3097.4   296.5  3043.5
   306.4 3035.59   316.3 3025.91   345.9 2994.55   355.8 2985.82   365.7  2978.5
   375.6  2972.6   385.5    2968   405.2 2961.32   424.52956.597   434.9 2955.94
   454.52958.702   474.6  2962.9   494.7 2964.43   524.9  2963.7   685.7 2963.68
   725.9 2964.43     736 2966.28     746 2969.32   856.6 3007.47     927 3030.57
#Mann= 3 , 0 , 0
       0      .1       0   424.5    .045       0   454.5      .1       0
Bank Sta=424.5,454.5
XS Rating Curve= 0 ,0
Exp/Cntr=0.3,0.1

Type RM Length L Ch R = 1 ,31785.2 ,369.7,373.7,377.4
XS GIS Cut Line= 3
     2104684.209      402817.011     2105119.863      402965.779
     2105551.411      403119.918
#Sta/Elev= 30
       0 3138.41      20 3128.65    80.1 3103.31   120.1 3085.26   160.1 3066.08
   270.2 3011.17   350.3 2974.61   370.3 2966.92   410.3 2954.59   430.3 2946.92
     4362945.506   440.3 2944.44   450.4 2944.16     4662946.208   480.3 2947.74
     560    2953   579.9 2954.75   609.8 2959.83   619.8 2962.49   629.7 2966.19
   639.7 2970.57   679.5 2988.73   719.4  3004.7   769.2 3026.36   789.1 3034.62
     809 3042.22   858.8 3060.31   888.7 3071.97   898.7 3075.42   918.6 3080.81
#Mann= 3 , 0 , 0
       0      .1       0     436    .045       0     466      .1       0
Bank Sta=436,466
XS Rating Curve= 0 ,0
Exp/Cntr=0.3,0.1

Type RM Length L Ch R = 1 ,31411.5 ,288.4,288.4,288.4
XS GIS Cut Line= 3
     2104558.717      403085.946     2104959.303      403304.147
     2105354.964      403526.896
#Sta/Elev= 30
       0 3129.19     9.9 3125.44    29.8  3117.2    59.5 3104.33    99.2 3086.38
   138.8 3068.12     238 3023.44   247.9  3018.1   257.8 3012.34   297.5 2987.56
   317.3 2975.47   337.2 2964.12   366.9 2947.88   386.7 2935.57   390.92933.978
   396.7 2931.78   406.6 2931.69   420.92933.314   426.4 2933.97   436.3 2934.56
   446.2 2934.72   526.8 2935.58   617.6 2935.93   627.7 2936.18   637.8 2937.59
   647.9 2940.31     668 2947.43   819.4 3004.71   859.8 3020.76   910.2 3041.83
#Mann= 3 , 0 , 0
       0      .1       0   390.9    .045       0   420.9      .1       0
Bank Sta=390.9,420.9
XS Rating Curve= 0 ,0
Exp/Cntr=0.3,0.1

Type RM Length L Ch R = 1 ,31123.1 ,256.1,266.6,277
XS GIS Cut Line= 3
      2104401.94      403328.726     2104802.526      403546.926
     2105198.187      403769.676
#Sta/Elev= 30
       0 3080.21    49.6 3066.22    79.3 3058.69   138.8 3045.02   168.6  3040.3
   178.5 3037.85   208.2 3028.43   228.1 3023.04     238 3019.42   267.8 3006.18
   317.3 2982.18   366.9 2959.91   376.8 2954.45   386.7 2947.92   406.6 2932.39
   417.72925.292   426.4 2922.04   436.3  2921.9   447.72923.469   466.2 2925.81
   486.4 2926.88   627.7 2929.12   688.2 2931.61   708.4 2933.05   718.5 2934.89
   738.7 2940.18   799.2 2957.78   859.8 2974.74   879.9 2979.19   910.2 2983.62
#Mann= 3 , 0 , 0
       0      .1       0   417.7    .045       0   447.7      .1       0
Bank Sta=417.7,447.7
XS Rating Curve= 0 ,0
Exp/Cntr=0.3,0.1

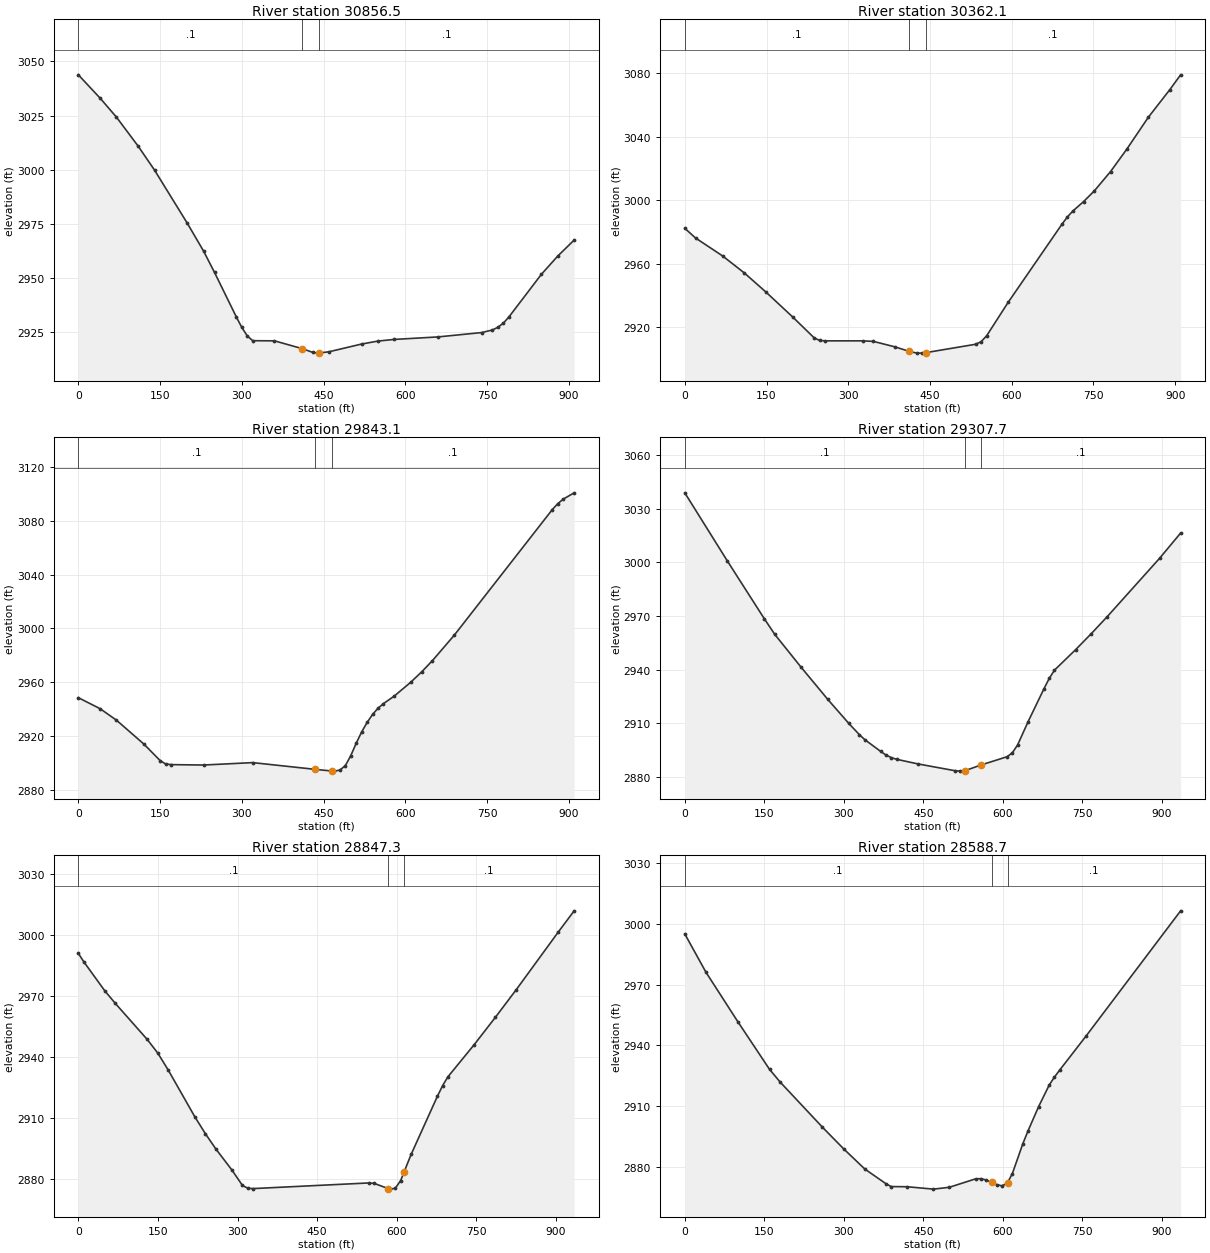
Type RM Length L Ch R = 1 ,30856.5 ,485.2,494.4,501.2
XS GIS Cut Line= 2
     2104394.836        403432.2     2104950.788      404152.628
#Sta/Elev= 30
       0 3043.79      40 3033.02      70 3024.24     110 3010.79     140 2999.74
     200 2975.26     230 2962.34     250 2952.53     290 2931.99     300 2927.17
     310 2923.27     320 2921.03     360 2920.96   411.32917.329     430 2915.65
     440 2915.29   441.32915.312     460 2915.92     520 2919.49     550 2920.86
     580 2921.62     660 2922.77     740 2924.78     760 2925.97     770 2927.23
     780 2929.13     790 2931.91     850 2951.72     880 2960.14     910  2967.5
#Mann= 3 , 0 , 0
       0      .1       0   411.3    .045       0   441.3      .1       0
Bank Sta=411.3,441.3
XS Rating Curve= 0 ,0
Exp/Cntr=0.3,0.1

Type RM Length L Ch R = 1 ,30362.1 ,518,519,519.9
XS GIS Cut Line= 3
     2104122.479      403504.499     2104287.894      403928.365
      2104453.31      404352.231
#Sta/Elev= 30
       0 2982.37    19.8 2976.24    69.2 2965.03   108.8 2954.42   148.4 2942.45
   197.8 2926.67   237.4  2913.5   247.3 2911.86   257.2  2911.6   326.4  2911.6
   346.2 2911.26   385.8  2907.8   412.22904.966   425.3 2903.95   434.7 2903.88
   442.22904.177   534.1 2909.47     544 2911.13   553.9 2914.74   593.5 2935.83
   692.4 2985.03   702.3 2989.54   712.2 2993.24     732 2999.18   751.7 3005.91
   781.4 3018.03   811.1 3032.06   850.6 3052.11   890.2 3069.55     910 3078.85
#Mann= 3 , 0 , 0
       0      .1       0   412.2    .045       0   442.2      .1       0
Bank Sta=412.2,442.2
XS Rating Curve= 0 ,0
Exp/Cntr=0.3,0.1

Type RM Length L Ch R = 1 ,29843.1 ,545.3,535.4,525.6
XS GIS Cut Line= 2
     2103640.879      403659.786     2103971.711      404507.519
#Sta/Elev= 30
       0 2948.63      40 2940.45      70 2931.92     120  2914.3     150 2901.99
     160 2899.44     170 2898.93     230 2898.63     320 2900.42   434.82895.412
   464.82894.199     470  2894.1     480 2894.89     490 2898.13     500 2905.57
     510 2914.81     520 2923.21     530 2930.24     540 2936.16     550 2940.79
     560 2944.23     580 2949.87     610 2960.08     630 2967.74     650 2976.19
     690 2995.04     870 3088.35     880 3092.69     890 3096.08     910 3100.73
#Mann= 3 , 0 , 0
       0      .1       0   434.8    .045       0   464.8      .1       0
Bank Sta=434.8,464.8
XS Rating Curve= 0 ,0
Exp/Cntr=0.3,0.1

Type RM Length L Ch R = 1 ,29307.7 ,465.6,460.4,455.1
XS GIS Cut Line= 3
     2102961.559      403897.714     2103278.778      404215.883
     2103622.496      404559.536
#Sta/Elev= 30
       0 3038.86    79.9 3000.91   149.8  2968.5   169.7 2959.67   219.6  2941.2
   269.6 2923.32   309.5 2909.79   329.5  2903.5   339.5 2900.76   369.4 2894.19
   379.4 2892.17   389.4 2890.72   399.4 2889.77   439.3  2887.2   508.8 2883.42
   518.7 2883.14     5292883.446     5592886.592     608  2891.2   617.9 2893.39
   627.8  2897.8   647.7 2910.88   677.4 2929.16   687.4    2935   697.3 2939.63
     737 2951.04   766.7 2960.04   796.5 2969.47   895.6 3002.22   935.3 3016.36
#Mann= 3 , 0 , 0
       0      .1       0     529    .045       0     559      .1       0
Bank Sta=529,559
XS Rating Curve= 0 ,0
Exp/Cntr=0.3,0.1

Type RM Length L Ch R = 1 ,28847.3 ,258.5,258.6,258.6
XS GIS Cut Line= 3
     2102582.998      404347.165     2102964.129      404584.167
     2103376.882      404839.925
#Sta/Elev= 30
       0 2991.07      10 2987.02    49.9  2972.6    69.8 2966.39   129.7 2948.71
   149.6    2942   169.6 2933.52   219.4 2910.64   239.4 2902.27   259.3 2894.69
   289.2 2884.45   309.2 2876.82   319.2  2875.4   329.1 2875.22   547.9 2878.01
   557.8 2877.76   583.9 2875.24   587.5 2874.96   597.4  2875.4   607.4 2879.18
   613.92883.428   627.2 2892.08   676.7  2920.7   686.6 2925.97   696.6  2930.3
   746.1 2946.13   785.7 2959.48   825.4 2973.22   904.6 3001.61   934.4    3012
#Mann= 3 , 0 , 0
       0      .1       0   583.9    .045       0   613.9      .1       0
Bank Sta=583.9,613.9
XS Rating Curve= 0 ,0
Exp/Cntr=0.3,0.1

Type RM Length L Ch R = 1 ,28588.7 ,334.8,337.5,340.3
XS GIS Cut Line= 3
     2102417.224      404540.956     2102797.685       404779.93
     2103209.682      405037.802
#Sta/Elev= 30
       0 2995.01    39.9  2976.1    99.8 2951.75   159.8 2928.14   179.7 2921.89
   259.6 2899.56   299.5  2888.9   339.5  2878.9   379.4 2871.64   389.4 2870.22
   419.3 2870.14   469.1 2868.96   498.9 2869.86   548.5 2874.03   558.4 2874.12
   568.3 2873.49   578.82872.309   588.2 2871.19   598.1  2870.6     608 2871.74
   608.82872.136   617.9 2876.64   637.8 2891.48   647.7 2897.88   667.5 2909.76
   687.4 2920.36   697.3 2924.33   707.2 2927.77   756.8 2944.53   935.3 3006.42
#Mann= 3 , 0 , 0
       0      .1       0   578.8    .045       0   608.8      .1       0
Bank Sta=578.8,608.8
XS Rating Curve= 0 ,0
Exp/Cntr=0.3,0.1

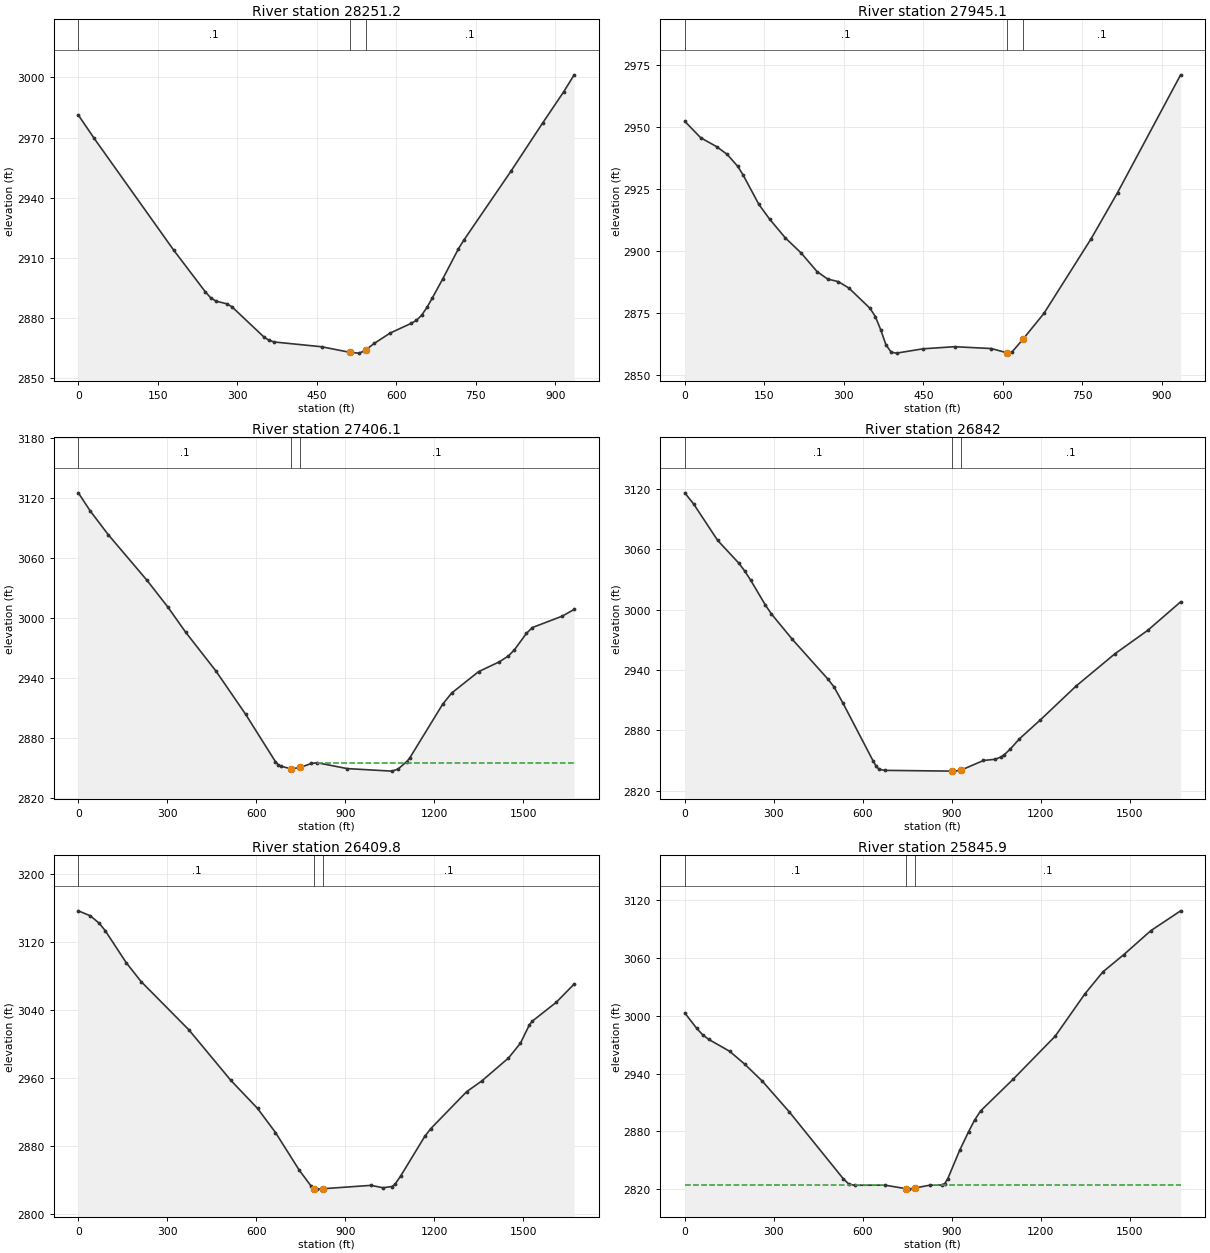
Type RM Length L Ch R = 1 ,28251.2 ,308.6,306.1,303.5
XS GIS Cut Line= 3
     2102257.003      404745.607     2102605.498      405029.174
     2102982.991      405335.342
#Sta/Elev= 30
       0  2981.2      30 2969.54   179.7 2913.96   239.6 2893.11   249.6 2890.17
   259.6 2888.49   279.6 2887.19   289.5 2885.73   349.4  2870.8   359.4 2869.01
   369.4 2868.14   459.2 2865.75   512.72862.941   528.6 2862.58   538.6  2863.5
   542.72864.303   558.4 2867.46   588.2 2872.58   627.8  2877.4   637.8 2878.92
   647.7 2881.51   657.6 2885.36   667.5 2889.94   687.4 2899.57   717.1 2914.61
     727 2918.81   816.3 2953.31   875.8 2977.22   915.5 2992.76   935.3 3001.24
#Mann= 3 , 0 , 0
       0      .1       0   512.7    .045       0   542.7      .1       0
Bank Sta=512.7,542.7
XS Rating Curve= 0 ,0
Exp/Cntr=0.3,0.1

Type RM Length L Ch R = 1 ,27945.1 ,542,539,535.9
XS GIS Cut Line= 3
     2102040.166      405024.364     2102420.626      405263.339
     2102832.623       405521.21
#Sta/Elev= 30
       0 2952.11      30 2945.49    59.9 2941.92    79.9 2938.81    99.8 2933.99
   109.8 2930.57   139.8  2918.6   159.8 2912.74   189.7 2905.12   219.6 2899.02
   249.6 2891.52   269.6 2888.52   289.5 2887.51   309.5 2884.92   349.4 2876.74
   359.4 2873.44   369.4 2868.19   379.4 2862.06   389.4 2859.05   399.4 2858.68
   449.3 2860.42   508.8 2861.27   578.2 2860.53   607.72858.815   617.9 2859.31
   637.72864.232   677.4 2874.68   766.7 2904.86   816.3 2923.37   935.3 2970.85
#Mann= 3 , 0 , 0
       0      .1       0   607.7    .045       0   637.7      .1       0
Bank Sta=607.7,637.7
XS Rating Curve= 0 ,0
Exp/Cntr=0.3,0.1

Type RM Length L Ch R = 1 ,27406.1 ,556.6,564.1,571.6
XS GIS Cut Line= 2
     2101478.955      405354.641     2102997.439      406051.401
#Sta/Elev= 30
       0 3125.09    40.3 3106.91   100.6 3083.31   231.5 3037.54   301.9 3010.74
   362.3  2985.4     463 2947.13   563.6 2903.63   664.3 2856.15   674.3 2852.98
   684.4 2851.49   717.22849.008   747.22850.352     785 2854.38   805.2 2855.11
   905.8 2849.25  1056.8 2846.72  1076.9 2848.73  1107.1 2856.35  1117.2 2860.13
  1227.9 2913.78  1258.1 2924.85  1348.6  2946.2  1419.1 2956.14  1449.3 2961.98
  1469.4 2968.05  1509.7 2984.44  1529.8 2990.33  1630.4 3001.73  1670.7 3008.47
#Mann= 3 , 0 , 0
       0      .1       0   717.2    .045       0   747.2      .1       0
#XS Ineff= 2 , 0
                          803.54         2855.26
Permanent Ineff=
       F       F
Bank Sta=717.2,747.2
XS Rating Curve= 0 ,0
Exp/Cntr=0.3,0.1

Type RM Length L Ch R = 1 ,26842   ,432.2,432.2,432.2
XS GIS Cut Line= 2
     2101468.037      405585.549      2102693.23      406721.405
#Sta/Elev= 30
       0 3116.17    30.2 3104.91   110.7 3068.87   181.2 3046.52   201.3 3038.69
   221.4 3029.57   271.7 3004.51   291.9 2995.73   362.3  2970.5   483.1 2930.64
   503.2 2922.95   533.4 2906.79   634.1 2849.83   644.1 2844.67   654.2 2841.29
   674.3 2840.19   899.22839.433   905.8 2839.42   929.22840.206  1006.4 2850.01
  1046.7 2851.24  1066.8 2853.72  1076.9 2855.86    1097 2861.45  1127.2 2871.43
  1197.7 2890.26  1318.4 2924.01  1449.3 2956.12    1560 2979.44  1670.7 3007.76
#Mann= 3 , 0 , 0
       0      .1       0   899.2    .045       0   929.2      .1       0
Bank Sta=899.2,929.2
XS Rating Curve= 0 ,0
Exp/Cntr=0.3,0.1

Type RM Length L Ch R = 1 ,26409.8 ,559.2,563.9,568.7
XS GIS Cut Line= 2
     2101176.136      405851.524     2102401.329       406987.38
#Sta/Elev= 30
       0 3156.81    40.3 3150.98    70.4 3142.19    90.6 3133.52     161 3096.02
   211.4 3073.67   372.4  3016.9   513.3 2957.66   603.9 2924.45   664.3 2896.13
   744.8 2851.64     785 2832.84   794.82830.133   805.2 2829.54   824.82830.025
   986.3 2833.98  1026.6 2831.16  1056.8 2832.62  1066.8 2835.09    1087  2845.5
  1167.5 2891.66  1187.6 2900.71  1308.4 2944.11  1358.7 2956.54  1449.3 2983.69
  1489.6 3001.11  1519.7 3022.63  1529.8 3027.11  1610.3 3049.22  1670.7 3070.73
#Mann= 3 , 0 , 0
       0      .1       0   794.8    .045       0   824.8      .1       0
Bank Sta=794.8,824.8
XS Rating Curve= 0 ,0
Exp/Cntr=0.3,0.1

Type RM Length L Ch R = 1 ,25845.9 ,275.1,271.1,266.7
XS GIS Cut Line= 2
     2100972.962      406219.043      2101972.36      407557.875
#Sta/Elev= 30
       0 3002.84    40.3 2986.81    60.4 2980.14    80.5 2975.46     151 2963.08
   201.3 2949.91   261.7 2931.92   352.3 2900.08   533.4 2831.01   553.6 2824.97
   573.7 2823.99   674.3 2824.13   744.8 2820.45   754.8 2819.98   774.82821.135
   825.3 2824.06   865.6 2824.27   875.6 2825.71   885.7  2830.5   925.9 2860.08
   956.1 2879.52   976.3 2891.53   996.4 2901.06  1107.1 2934.31    1248 2978.73
  1348.6 3022.86    1409 3045.56  1479.5 3063.49  1570.1 3088.24  1670.7 3108.88
#Mann= 3 , 0 , 0
       0      .1       0   744.8    .045       0   774.8      .1       0
#XS Ineff= 2 , 0
          672.23 2824.26  836.47         2824.53
Permanent Ineff=
       F       F
Bank Sta=744.8,774.8
XS Rating Curve= 0 ,0
Exp/Cntr=0.3,0.1

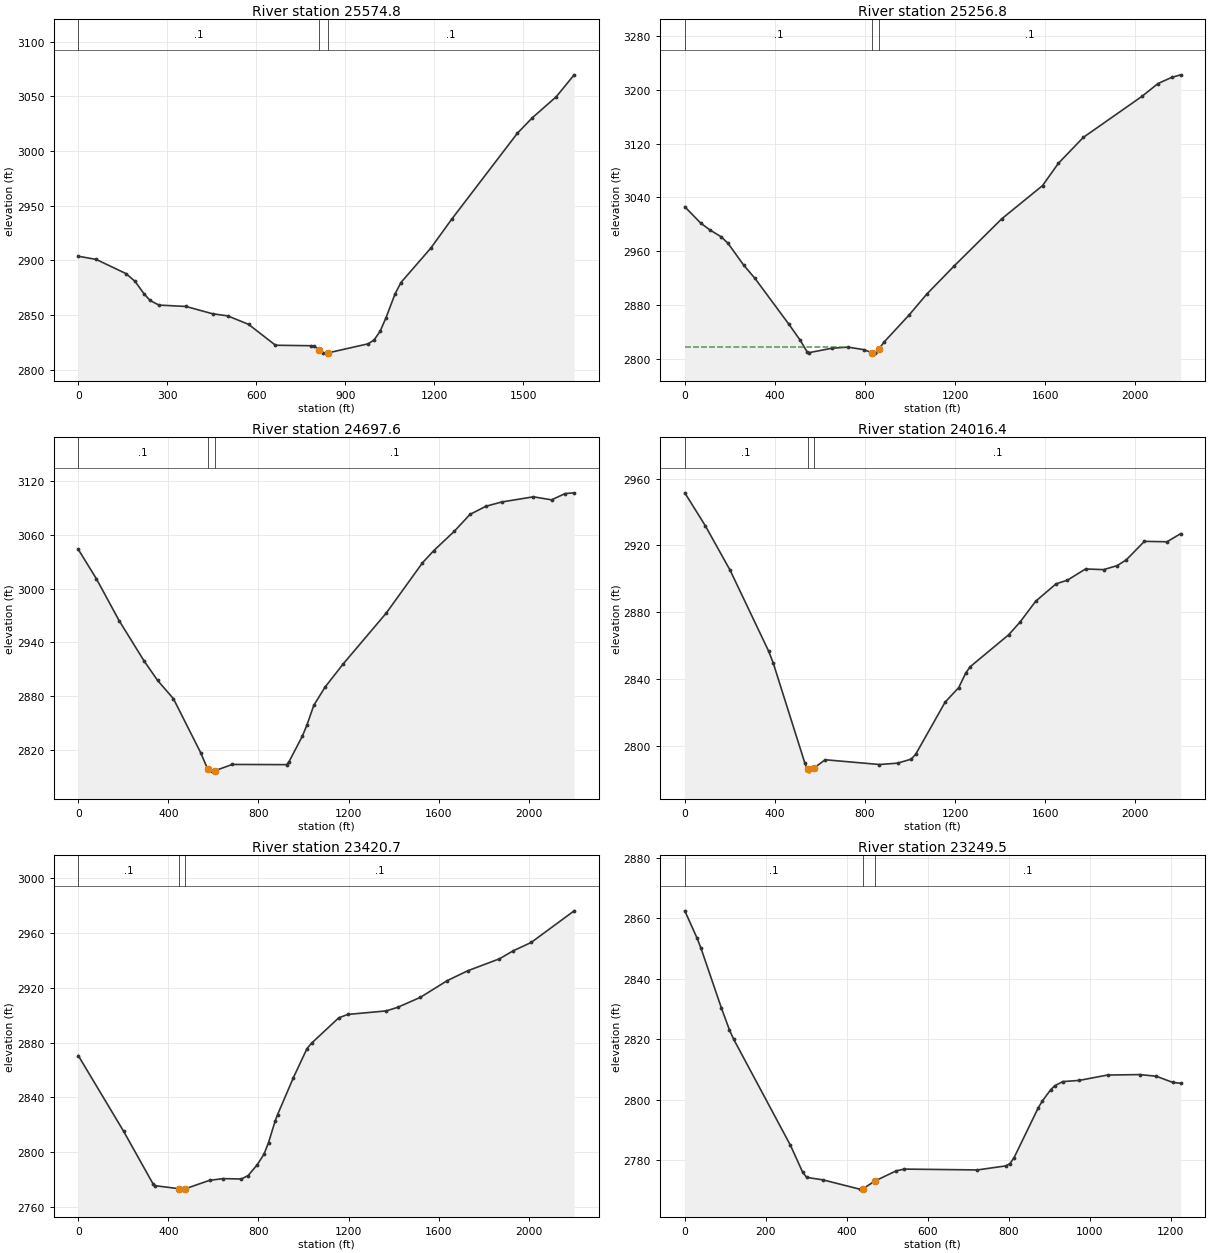
Type RM Length L Ch R = 1 ,25574.8 ,322.3,318,313.7
XS GIS Cut Line= 2
      2100585.29      406405.089     2101854.604      407491.417
#Sta/Elev= 30
       0 2903.67    60.4 2900.74     161 2887.72   191.2 2880.65   221.4  2869.3
   241.6 2863.22   271.7 2858.97   362.3 2857.72   452.9 2850.99   503.2  2849.1
   573.7 2841.34   664.3 2822.22     785 2821.78   795.1 2821.34   810.12818.254
   825.3 2815.27   835.4 2815.01   840.1 2815.17   976.3 2823.51   996.4 2827.01
  1016.5 2834.84  1036.6  2847.3  1066.8 2868.95    1087 2879.61  1187.6 2911.08
  1258.1 2937.56  1479.5 3016.26  1529.8 3030.37  1610.3  3049.6  1670.7 3069.66
#Mann= 3 , 0 , 0
       0      .1       0   810.1    .045       0   840.1      .1       0
Bank Sta=810.1,840.1
XS Rating Curve= 0 ,0
Exp/Cntr=0.3,0.1

Type RM Length L Ch R = 1 ,25256.8 ,559.9,559.2,557.8
XS GIS Cut Line= 2
     2100393.623      406803.514     2102274.823      407947.714
#Sta/Elev= 30
       0 3026.19    70.4  3002.1   110.6 2992.04   160.9  2981.8     191  2972.4
   261.4 2939.69   311.7 2919.93   462.5 2851.82   512.8 2828.07   542.9 2811.14
     553 2809.88   653.5 2816.37   723.9 2818.02   794.3 2814.31     8312809.759
   844.5  2809.1   854.6 2811.59     8612814.777   884.8 2825.52   995.4 2865.43
  1075.8 2897.11  1196.4 2938.47  1407.6 3008.38  1588.5 3057.58  1658.9 3090.63
  1769.5 3129.06  2030.9 3190.17  2101.3 3209.01  2161.6 3218.03  2201.8 3221.92
#Mann= 3 , 0 , 0
       0      .1       0     831    .045       0     861      .1       0
#XS Ineff= 2 , 0
          723.12 2818.03
Permanent Ineff=
       F       F
Bank Sta=831,861
XS Rating Curve= 0 ,0
Exp/Cntr=0.3,0.1

Type RM Length L Ch R = 1 ,24697.6 ,684.5,680.9,677.9
XS GIS Cut Line= 2
     2100158.222      407278.572     2102066.052      408377.796
#Sta/Elev= 30
       0 3043.91    80.4 3010.98     181 2964.31   291.6 2919.29   351.9 2897.41
   422.3 2876.91   542.9 2816.69   573.1 2798.96   576.52798.073   593.2 2795.88
   606.52796.339   683.7 2803.36     925 2803.14     935 2806.11   995.4 2835.34
  1015.5 2847.68  1045.6 2869.49  1095.9 2889.97  1176.3 2915.88  1367.4 2972.72
  1528.2 3028.93  1578.5 3042.61    1669 3064.08  1739.4 3083.13  1809.7 3092.18
  1880.1    3097  2020.9 3102.78  2101.3 3099.38  2161.6 3106.41  2201.8 3107.24
#Mann= 3 , 0 , 0
       0      .1       0   576.5    .045       0   606.5      .1       0
Bank Sta=576.5,606.5
XS Rating Curve= 0 ,0
Exp/Cntr=0.3,0.1

Type RM Length L Ch R = 1 ,24016.4 ,587.6,595.6,603.7
XS GIS Cut Line= 2
     2099873.596      407973.759     2101928.346      408765.029
#Sta/Elev= 30
       0 2951.49    90.5 2931.89   201.1 2905.12     372 2856.69   392.1 2849.75
   532.9  2789.6   545.12785.699     553 2784.69   575.1 2786.66   623.4 2791.51
   864.6 2788.66   945.1 2789.47  1005.4 2791.87  1025.5 2794.83  1156.2 2826.08
  1216.5 2834.76  1246.7 2843.28  1266.8 2847.21  1437.7 2866.36    1488 2873.91
  1558.4 2886.55  1648.9 2896.98  1699.1 2899.14  1779.6 2905.86    1860 2905.46
  1920.3 2907.88  1960.5 2911.31    2041 2922.41  2141.5 2922.16  2201.8 2927.02
#Mann= 3 , 0 , 0
       0      .1       0   545.1    .045       0   575.1      .1       0
#XS Ineff= 2 , 0
                          625.63         2791.48
Permanent Ineff=
       F       F
Bank Sta=545.1,575.1
XS Rating Curve= 0 ,0
Exp/Cntr=0.3,0.1

Type RM Length L Ch R = 1 ,23420.7 ,167,171.2,175.4
XS GIS Cut Line= 2
     2099875.332      408421.625     2101563.544      409835.149
#Sta/Elev= 30
       0  2870.4   201.1 2815.22   331.8 2776.86   341.8 2775.53   445.62773.357
   462.5 2773.03   475.62773.326   583.1 2779.47   643.5  2780.7   723.9 2780.41
   754.1 2782.97   794.3 2790.78   824.4 2798.51   844.5 2806.93   874.7 2823.08
   884.8 2827.41   955.1 2854.41  1015.5 2875.58  1035.6 2879.49  1156.2 2897.99
  1196.4 2900.48  1367.4 2903.06  1417.6 2905.65  1518.2 2912.89  1638.8 2925.19
  1729.3 2932.34  1870.1 2941.07  1930.4 2946.85  2010.8 2952.98  2201.8 2976.07
#Mann= 3 , 0 , 0
       0      .1       0   445.6    .045       0   475.6      .1       0
Bank Sta=445.6,475.6
XS Rating Curve= 0 ,0
Exp/Cntr=0.3,0.1

Type RM Length L Ch R = 1 ,23249.5 ,687,686,685
XS GIS Cut Line= 2
     2099839.011      408516.218     2100639.007      409443.432
#Sta/Elev= 30
       0  2862.4    30.1 2853.44    40.2 2849.96    90.3 2830.34   110.4    2823
   120.5 2820.03     261 2784.92   291.1 2776.04   301.1 2774.33   341.3 2773.52
   431.6 2770.46   440.52770.645   470.52773.199     522 2776.49     542 2777.08
   722.7  2776.8     793 2778.14     803 2778.89   813.1 2780.83   873.3 2797.41
   883.3 2799.61   903.4 2803.25   913.4 2804.57   933.5 2805.99   973.7 2806.37
    1044 2808.15  1124.2  2808.3  1164.4 2807.76  1204.6 2805.74  1224.6 2805.42
#Mann= 3 , 0 , 0
       0      .1       0   440.5    .045       0   470.5      .1       0
Bank Sta=440.5,470.5
XS Rating Curve= 0 ,0
Exp/Cntr=0.3,0.1

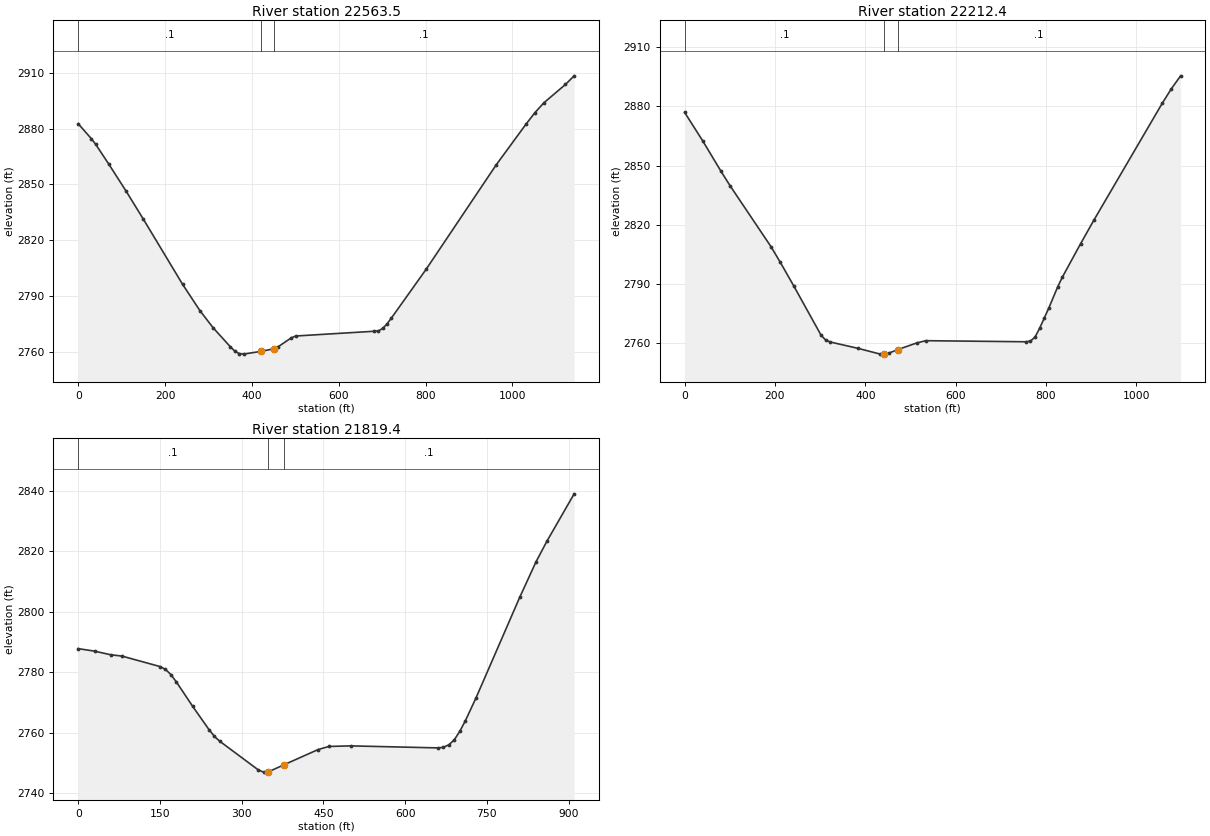
Type RM Length L Ch R = 1 ,22563.5 ,350.9,351.1,351.3
XS GIS Cut Line= 2
     2099360.541      408975.526     2100122.951      409825.822
#Sta/Elev= 30
       0 2882.68      30 2874.72    40.1 2871.65    70.1 2861.05   110.2 2846.42
   150.3 2831.19   240.4 2796.21   280.5 2781.98   310.6 2772.84   350.6 2762.54
   360.6 2760.27   370.7 2758.91   380.7 2758.64     4212760.137     4512761.543
   460.8 2762.67   490.9 2767.45   500.9  2768.4   681.2 2770.95   691.2 2771.16
   701.3 2772.48   711.3 2774.98   721.3  2778.1   801.4  2804.4   961.7 2860.28
  1031.8 2882.67  1051.9  2888.7  1071.9 2893.88    1122 2903.84    1142 2908.48
#Mann= 3 , 0 , 0
       0      .1       0     421    .045       0     451      .1       0
Bank Sta=421,451
XS Rating Curve= 0 ,0
Exp/Cntr=0.3,0.1

Type RM Length L Ch R = 1 ,22212.4 ,397.9,392.9,388
XS GIS Cut Line= 2
     2099070.873      409175.425     2099804.005      409993.067
#Sta/Elev= 30
       0 2876.87    40.3 2862.37    80.6 2847.05   100.8  2839.7   191.4 2808.89
   211.6 2801.12   241.8 2789.01   302.2 2764.12   312.3 2761.73   322.4 2760.75
   382.9  2757.6   433.2 2754.62   442.12754.682   453.4 2755.25   472.12756.934
   513.8 2760.27     534 2761.42   755.6 2760.87   765.7 2761.21   775.8 2763.24
   785.9 2767.65   795.9 2772.66     806 2777.78   826.2 2788.75   836.2 2793.52
   876.5  2810.4   906.8 2822.66  1057.9 2881.67    1078 2888.95  1098.2  2895.4
#Mann= 3 , 0 , 0
       0      .1       0   442.1    .045       0   472.1      .1       0
Bank Sta=442.1,472.1
XS Rating Curve= 0 ,0
Exp/Cntr=0.3,0.1

Type RM Length L Ch R = 1 ,21819.4 ,297.7,310.7,323.6
XS GIS Cut Line= 2
     2098802.743      409582.946      2099550.66      410101.328
#Sta/Elev= 30
       0 2787.81      30 2786.98      60 2785.77      80 2785.36     150  2781.9
     160 2780.98     170 2779.25     180 2776.84     210 2768.76     240 2761.06
     250 2758.81     260 2757.19     330 2747.82     340 2747.03   347.92747.046
   377.92749.483     440 2754.47     460 2755.51     500  2755.7     660 2755.03
     670 2755.22     680 2756.05     690 2757.68     700 2760.46     710 2763.85
     730 2771.57     810 2804.71     840 2816.47     860 2823.28     910 2838.93
#Mann= 3 , 0 , 0
       0      .1       0   347.9    .045       0   377.9      .1       0
Bank Sta=347.9,377.9
XS Rating Curve= 0 ,0
Exp/Cntr=0.3,0.1