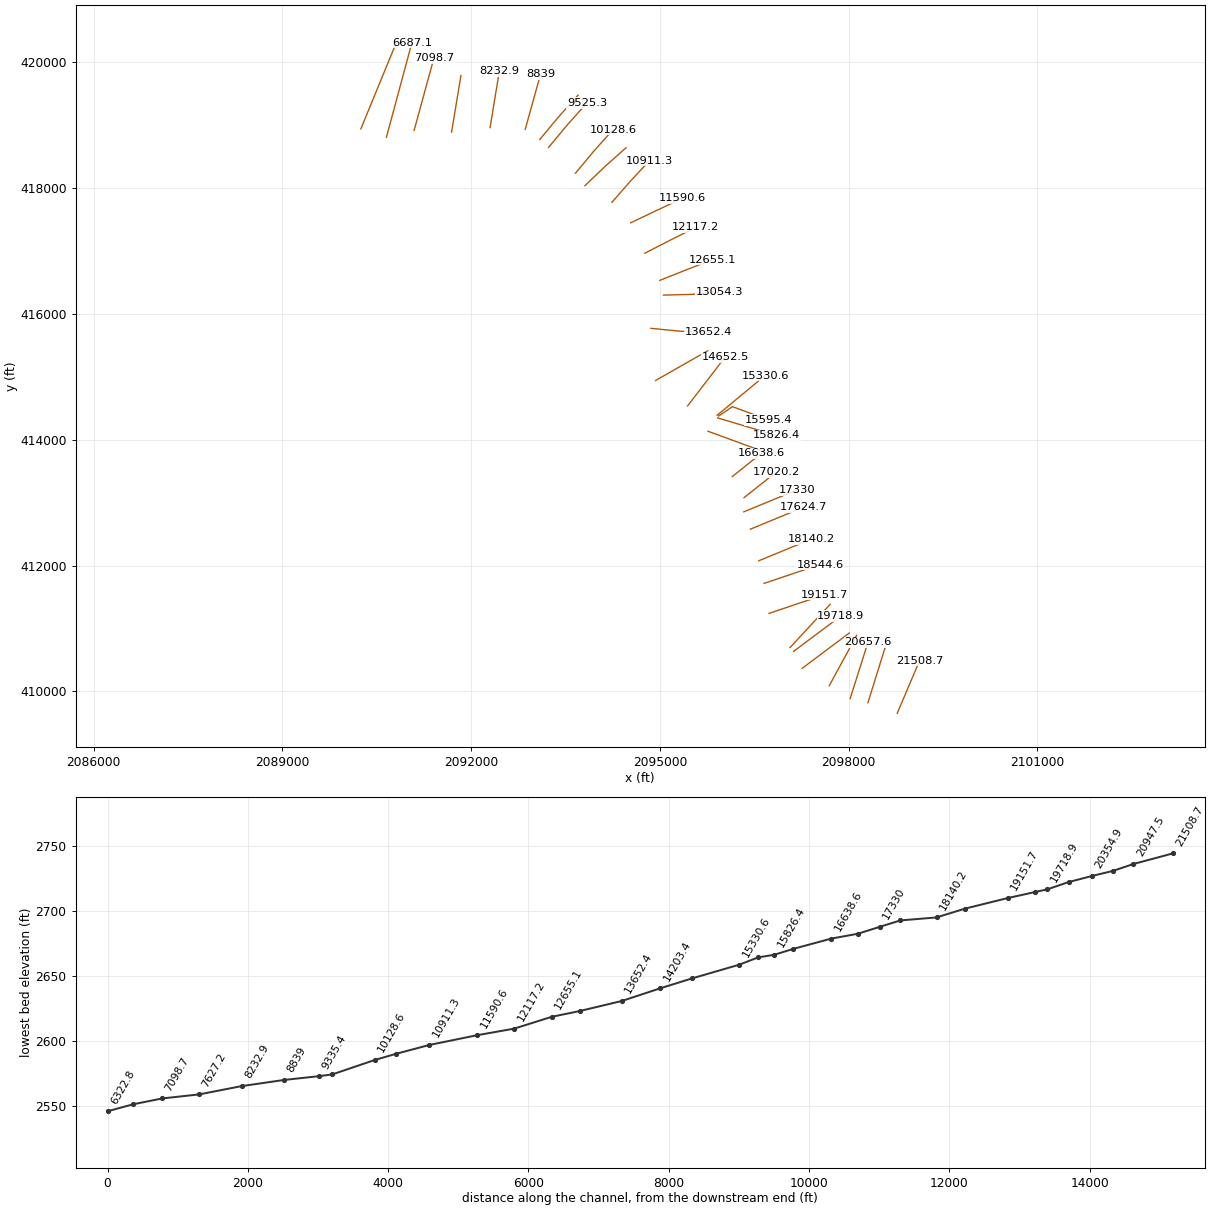
HEC-RAS study LaurCk.prj: LaurCk

--- LaurCk.g01 (geometry) --- (continued)

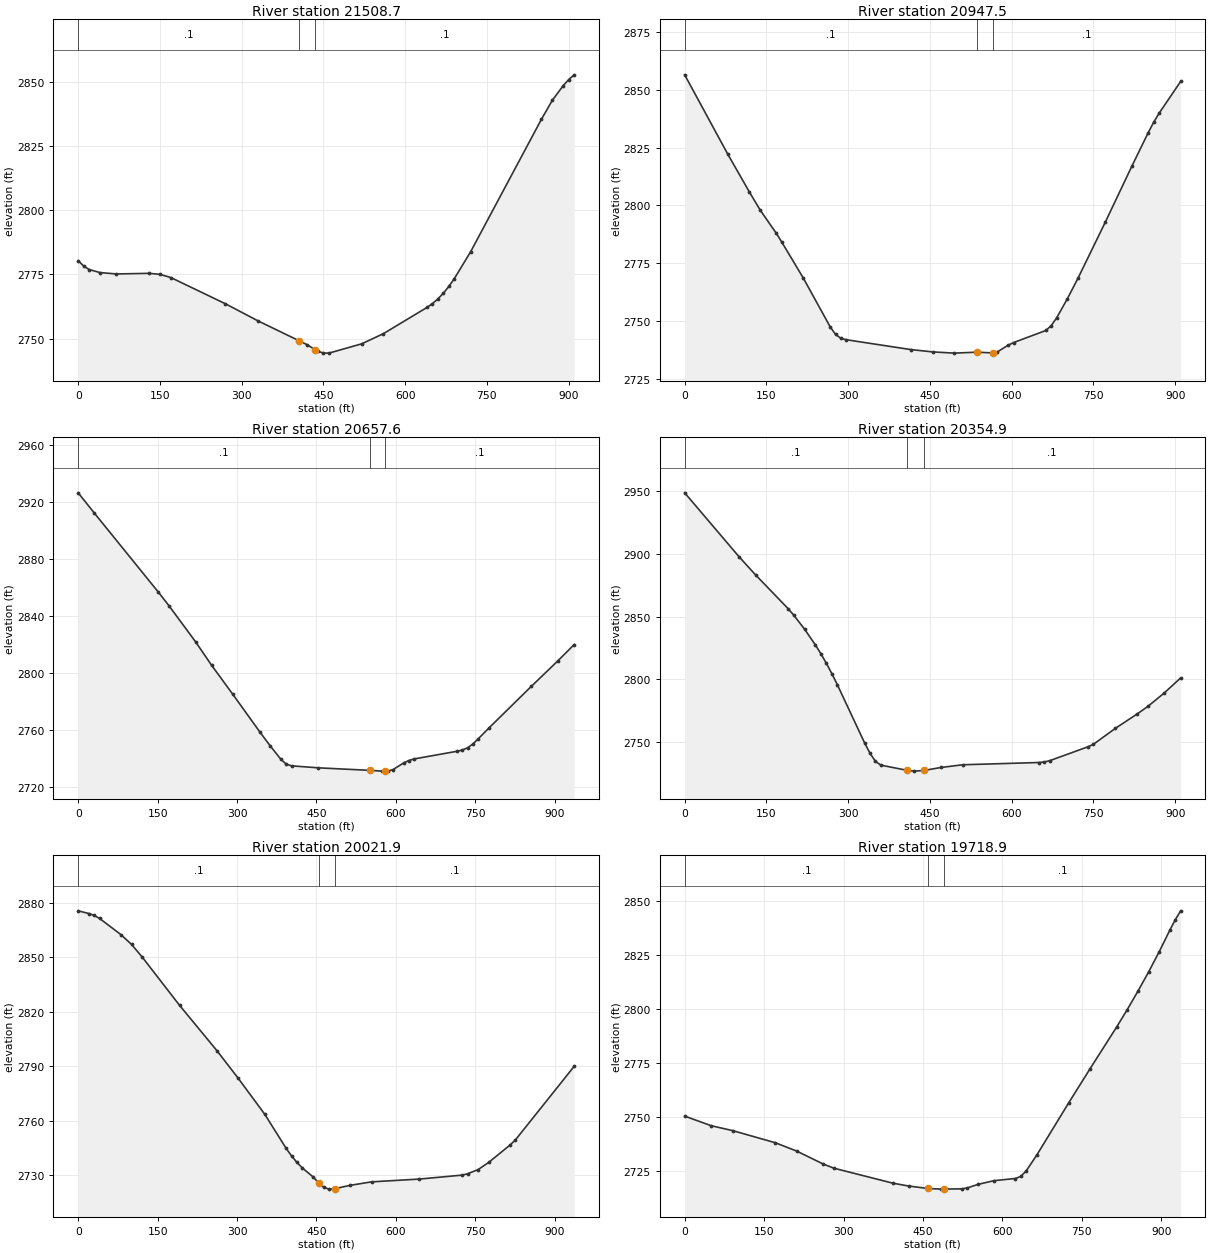
Type RM Length L Ch R = 1 ,21508.7 ,559.4,561.2,563.1
XS GIS Cut Line= 2
     2098770.123      409652.137     2099126.506       410489.45
#Sta/Elev= 30
       0 2780.35      10 2778.31      20 2776.93      40 2775.74      70  2775.2
     130 2775.44     150 2775.05     170  2773.8     270  2763.6     330 2756.92
   404.52749.269     420 2747.64   434.52745.759     440 2745.06     450  2744.4
     460 2744.37     520 2747.98     560 2751.95     640 2762.17     650 2763.65
     660 2765.49     670 2767.71     680 2770.32     690 2773.34     720 2783.83
     850 2835.45     870 2842.84     890 2848.56     900 2850.89     910 2852.75
#Mann= 3 , 0 , 0
       0      .1       0   404.5    .045       0   434.5      .1       0
Bank Sta=404.5,434.5
XS Rating Curve= 0 ,0
Exp/Cntr=0.3,0.1

Type RM Length L Ch R = 1 ,20947.5 ,290.1,289.9,289.7
XS GIS Cut Line= 3
     2098304.832      409821.702     2098440.582       410255.98
     2098576.332      410690.258
#Sta/Elev= 30
       0 2856.43    79.1 2822.15   118.7 2805.84   138.5 2798.03   168.2 2787.96
     178 2784.25   217.6 2768.68   267.1 2747.54     277 2744.28   286.8 2742.61
   296.7 2742.01   415.4 2737.75     455 2736.76   494.6 2736.23   535.52736.636
   565.52736.328   573.7 2736.75   593.5 2739.66   603.4 2740.78   662.7 2746.01
   672.6 2748.12   682.5 2751.45   702.3 2759.76   722.1 2768.79   771.5 2792.66
     821  2817.2   850.6 2831.47   860.5 2835.91   870.4 2839.79     910 2853.55
#Mann= 3 , 0 , 0
       0      .1       0   535.5    .045       0   565.5      .1       0
Bank Sta=535.5,565.5
XS Rating Curve= 0 ,0
Exp/Cntr=0.3,0.1

Type RM Length L Ch R = 1 ,20657.6 ,307.2,302.6,298.1
XS GIS Cut Line= 2
     2098022.437      409886.352     2098305.609      410779.243
#Sta/Elev= 30
       0 2926.38    30.2 2912.28   151.1 2856.78   171.2 2847.21   221.6 2821.81
   251.8 2805.37   292.1 2784.85   342.5 2758.75   362.6  2748.7   382.8 2739.27
   392.8 2735.92   402.9 2734.67   453.2 2733.28   550.22731.511   574.1 2730.96
   580.22730.978   584.2 2730.99   594.3 2731.96   614.4 2736.64   624.5 2738.42
   634.6 2739.53   715.1 2744.88   725.2 2745.73   735.3 2747.34   745.4 2750.03
   755.4 2753.59   775.6  2761.2   856.1 2790.59   906.5  2808.6   936.7 2819.84
#Mann= 3 , 0 , 0
       0      .1       0   550.2    .045       0   580.2      .1       0
Bank Sta=550.2,580.2
XS Rating Curve= 0 ,0
Exp/Cntr=0.3,0.1

Type RM Length L Ch R = 1 ,20354.9 ,342.7,333,323.4
XS GIS Cut Line= 2
     2097691.001      410092.486     2098125.833      410891.874
#Sta/Elev= 30
       0 2948.47     100 2897.49     130  2883.2     190 2856.22     200 2851.17
     220 2839.95     240 2827.32     250 2820.34     260 2812.78     270  2804.6
     280 2795.88     330 2749.58     340 2741.25     350 2734.76     360 2731.75
   408.82727.577     420 2726.99   438.82727.491     470 2729.88     510 2732.05
     650 2733.85     660 2734.26     670 2735.34     740 2746.36     750 2748.35
     790 2760.95     830 2772.41     850 2778.52     880 2789.21     910 2801.15
#Mann= 3 , 0 , 0
       0      .1       0   408.8    .045       0   438.8      .1       0
Bank Sta=408.8,438.8
XS Rating Curve= 0 ,0
Exp/Cntr=0.3,0.1

Type RM Length L Ch R = 1 ,20021.9 ,302.9,303,303.1
XS GIS Cut Line= 2
     2097259.754      410367.553     2098009.544       410929.03
#Sta/Elev= 30
       0 2875.42    20.1 2873.93    30.2 2872.87    40.3 2871.24    80.6 2862.35
   100.7 2856.96   120.9 2849.97   191.4 2823.44   261.9 2798.52   302.2 2783.29
   352.5 2763.42   392.8 2744.71   402.9 2740.62     413 2737.04     423 2734.04
   443.2 2729.14   454.22725.749   463.3 2723.37   473.4 2722.31   484.22722.543
   513.7  2724.4     554 2726.31   644.6 2727.85   725.2 2730.02   735.3 2730.73
   755.4 2733.08   775.6 2737.09   815.8 2746.61   825.9 2749.44   936.7 2789.86
#Mann= 3 , 0 , 0
       0      .1       0   454.2    .045       0   484.2      .1       0
Bank Sta=454.2,484.2
XS Rating Curve= 0 ,0
Exp/Cntr=0.3,0.1

Type RM Length L Ch R = 1 ,19718.9 ,174.8,178.8,182.9
XS GIS Cut Line= 2
     2097123.877      410636.365     2097873.668      411197.841
#Sta/Elev= 30
       0  2750.5    50.4 2746.04    90.6 2743.79   171.2 2738.18   211.5 2734.32
   261.9  2728.3     282 2726.38   392.8 2719.48     423 2718.13   459.92716.991
   483.5  2716.7   489.92716.745   523.8 2716.82   533.8 2717.26     554  2718.9
   584.2 2720.62   624.5 2721.62   634.6 2722.56   644.6 2724.99   664.8 2732.37
   725.2  2756.6   765.5 2772.38   815.8 2791.73     836 2799.86   856.1 2808.35
   876.3 2817.28   896.4 2826.68   916.6 2836.73   926.6 2841.39   936.7 2845.55
#Mann= 3 , 0 , 0
       0      .1       0   459.9    .045       0   489.9      .1       0
Bank Sta=459.9,489.9
XS Rating Curve= 0 ,0
Exp/Cntr=0.3,0.1

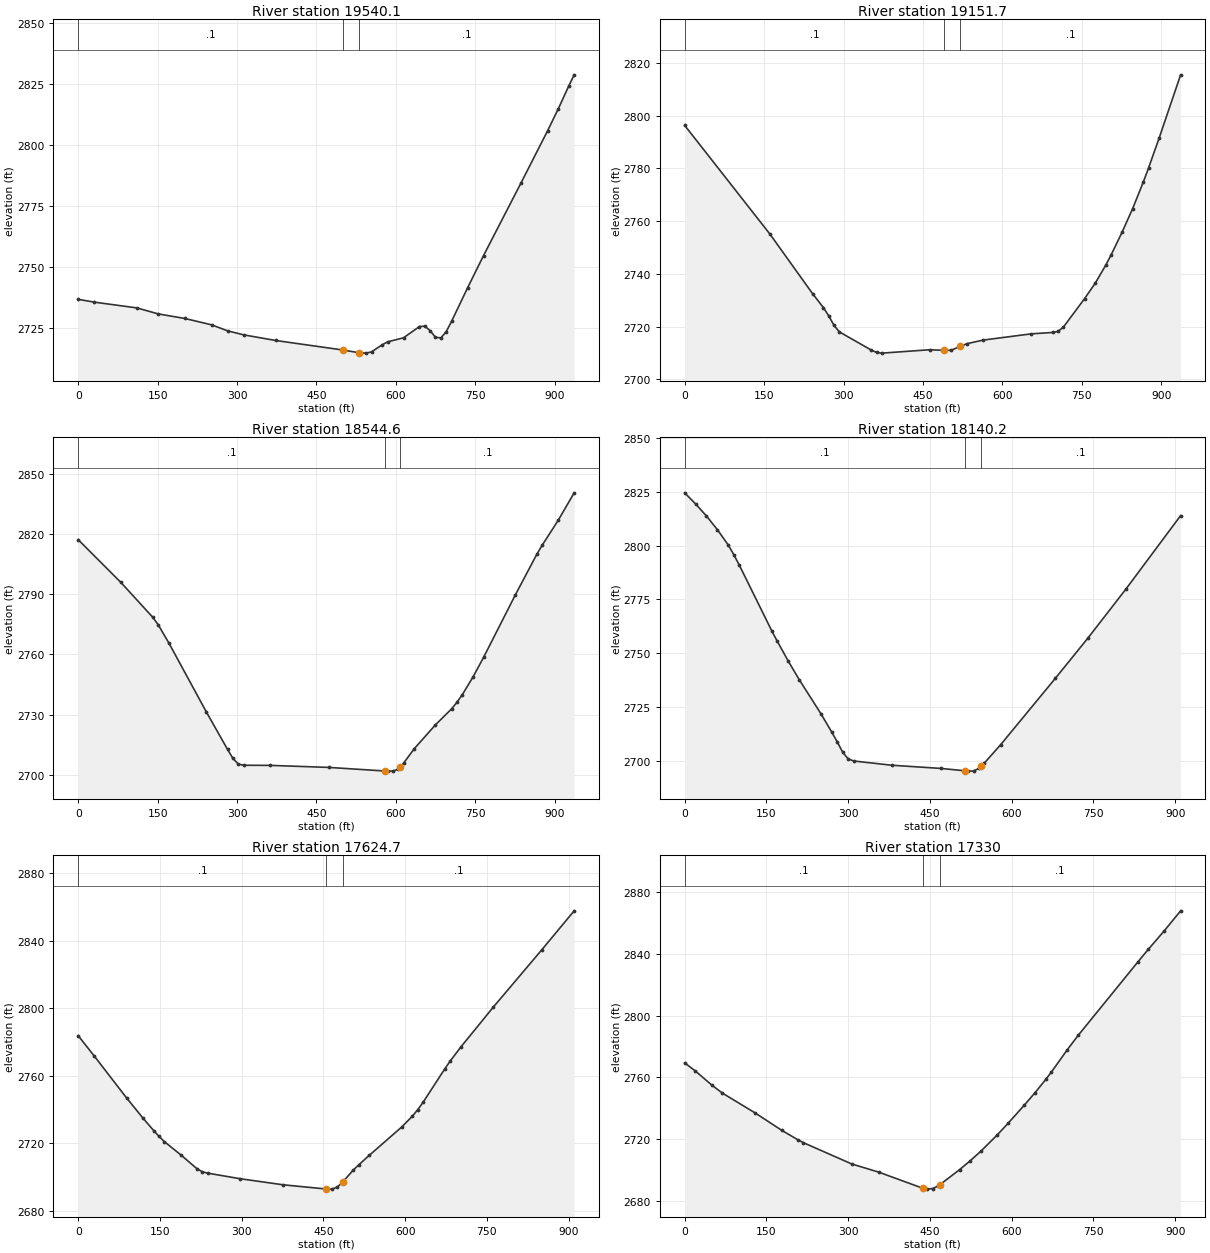
Type RM Length L Ch R = 1 ,19540.1 ,399.7,388.4,377
XS GIS Cut Line= 2
     2097066.942       410697.39     2097704.279      411383.862
#Sta/Elev= 30
       0  2736.7    30.2 2735.56   110.8 2733.18   151.1 2730.72   201.4 2728.84
   251.8 2726.24     282 2723.78   312.2 2722.13   372.7 2719.81   500.32715.878
   530.32714.775   543.9 2714.61     554 2715.14   574.1 2718.02   584.2 2719.24
   614.4  2720.9   644.6 2725.54   654.7 2725.69   664.8 2723.81   674.8 2721.12
   684.9 2720.86     695 2723.39   705.1 2727.64   735.3 2741.38   765.5 2754.66
     836 2784.37   886.4 2805.88   906.5 2814.83   926.6 2824.38   936.7 2828.91
#Mann= 3 , 0 , 0
       0      .1       0   500.3    .045       0   530.3      .1       0
Bank Sta=500.3,530.3
XS Rating Curve= 0 ,0
Exp/Cntr=0.3,0.1

Type RM Length L Ch R = 1 ,19151.7 ,607.2,607.1,606.9
XS GIS Cut Line= 2
      2096733.44      411240.784     2097621.634      411538.362
#Sta/Elev= 30
       0 2796.28   161.2 2755.04   241.7 2732.48   261.9 2727.26     272 2724.14
     282 2720.51   292.1 2718.04   352.5 2711.13   362.6 2710.22   372.7 2709.98
   463.3 2711.27   490.22711.009   503.6 2711.08   520.22712.517   533.8  2713.6
     564 2714.93   654.7 2717.29     695 2717.81   705.1 2718.23   715.1 2719.79
   755.4 2730.66   775.6 2736.53   795.7 2743.44   805.8 2747.35   825.9 2755.71
   846.1 2764.74   866.2 2774.81   876.3 2780.23   896.4 2791.63   936.7 2815.44
#Mann= 3 , 0 , 0
       0      .1       0   490.2    .045       0   520.2      .1       0
Bank Sta=490.2,520.2
XS Rating Curve= 0 ,0
Exp/Cntr=0.3,0.1

Type RM Length L Ch R = 1 ,18544.6 ,402.9,404.4,405.9
XS GIS Cut Line= 2
     2096653.503      411716.846     2097541.698      412014.425
#Sta/Elev= 30
       0 2817.19    80.6 2795.91     141 2778.48   151.1  2774.8   171.2 2765.73
   241.7 2731.52     282 2712.73   292.1 2708.27   302.2 2705.42   312.2 2704.81
   362.6 2704.74   473.4 2703.73   578.72701.951   584.2 2701.88   594.3 2701.88
   604.3 2702.86   608.72704.132   614.4 2705.78   634.6 2713.03   674.8 2724.96
   705.1 2732.88   715.1 2736.08   725.2 2739.87   745.4 2748.67   765.5  2758.5
   825.9 2789.84   866.2 2809.94   876.3 2814.44   906.5 2826.82   936.7 2840.55
#Mann= 3 , 0 , 0
       0      .1       0   578.7    .045       0   608.7      .1       0
Bank Sta=578.7,608.7
XS Rating Curve= 0 ,0
Exp/Cntr=0.3,0.1

Type RM Length L Ch R = 1 ,18140.2 ,515.5,515.5,515.5
XS GIS Cut Line= 2
     2096570.239      412075.812     2097411.696      412422.294
#Sta/Elev= 30
       0 2824.55      20 2819.41      40 2813.77      60 2807.42      80 2800.28
      90 2795.85     100 2791.05     160 2760.26     170 2755.47     190 2746.31
     210 2737.73     250 2721.81     270 2713.21     280  2708.7     290 2703.87
     300 2700.82     310 2699.84     380 2697.86     470 2696.38   514.32695.268
     520 2695.12     530 2695.17     540  2696.4   544.32697.475     550  2698.9
     580 2707.48     680 2738.24     740 2757.03     810 2779.91     910 2813.96
#Mann= 3 , 0 , 0
       0      .1       0   514.3    .045       0   544.3      .1       0
Bank Sta=514.3,544.3
XS Rating Curve= 0 ,0
Exp/Cntr=0.3,0.1

Type RM Length L Ch R = 1 ,17624.7 ,294.6,294.6,294.6
XS GIS Cut Line= 3
     2096437.132      412577.875     2096857.861      412751.116
     2097278.589      412924.357
#Sta/Elev= 30
       0 2783.81    29.7 2771.63      89  2746.8   118.7 2734.97   138.5 2727.53
   148.4 2724.05   158.3 2720.93   187.9 2713.23   217.6 2704.99   227.5 2703.14
   237.4 2702.31   296.7 2699.01   375.9 2695.39   455.32692.878   464.9 2692.82
   474.8 2693.88   485.3    2697   504.5 2704.05   514.4  2707.1   534.1 2712.88
   593.5 2729.62   613.3 2736.13   623.2 2740.01     633  2744.4   672.6  2764.1
   682.5 2768.73   702.3 2777.17   761.6 2800.72   850.6 2834.71     910 2857.82
#Mann= 3 , 0 , 0
       0      .1       0   455.3    .045       0   485.3      .1       0
Bank Sta=455.3,485.3
XS Rating Curve= 0 ,0
Exp/Cntr=0.3,0.1

Type RM Length L Ch R = 1 ,17330   ,303.3,309.8,316.4
XS GIS Cut Line= 3
     2096332.121      412852.987      2096752.85      413026.228
     2097173.578      413199.469
#Sta/Elev= 30
       0 2769.45    19.8 2764.14    49.5 2755.17    69.2 2749.91   128.6 2737.24
     178 2725.89   207.7 2719.75   217.6 2717.92   306.6 2704.12   356.1 2698.85
   437.62688.357   445.1 2687.88     455 2688.26   464.9 2689.88   467.62690.573
   504.5 2700.48   524.2 2706.28     544 2712.57   573.7 2722.95   593.5 2730.44
   623.2 2742.12   642.9 2750.19   662.7 2758.79   672.6 2763.37   702.3 2778.02
   722.1 2787.23   830.9 2834.34   850.6 2842.71   880.3 2854.86     910 2867.64
#Mann= 3 , 0 , 0
       0      .1       0   437.6    .045       0   467.6      .1       0
Bank Sta=437.6,467.6
XS Rating Curve= 0 ,0
Exp/Cntr=0.3,0.1

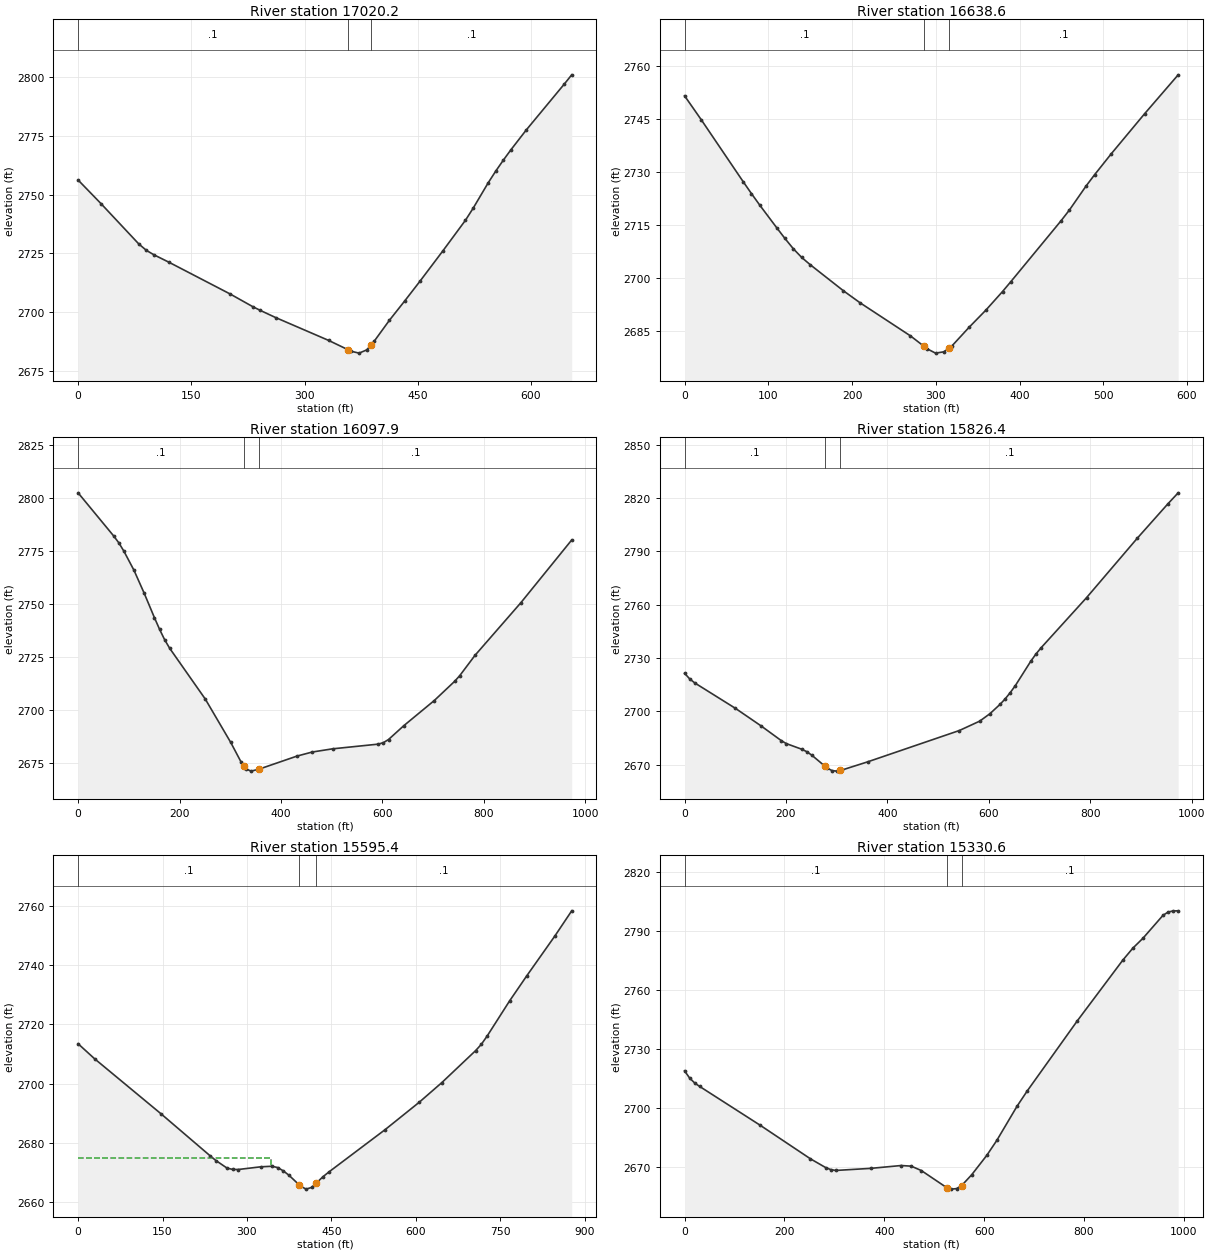
Type RM Length L Ch R = 1 ,17020.2 ,381.6,381.6,381.6
XS GIS Cut Line= 2
     2096335.515      413078.002     2096848.137      413484.156
#Sta/Elev= 30
       0 2756.23    30.2 2746.23    80.5    2729    90.6 2726.27   100.6  2724.4
   120.7  2721.2   201.2 2707.79   231.4 2702.36   241.5 2700.75   261.6 2697.74
     332 2687.99     358 2683.98   362.2 2683.35   372.3 2682.59   382.4 2683.96
     3882686.049   392.4 2687.69   412.5 2696.58   432.7 2704.77   452.8 2713.11
     483 2725.96   513.2  2739.1   523.2 2744.12   543.3 2755.01   553.4 2760.04
   563.5 2764.72   573.5 2769.11   593.6 2777.44     644 2796.98     654 2800.97
#Mann= 3 , 0 , 0
       0      .1       0     358    .045       0     388      .1       0
Bank Sta=358,388
XS Rating Curve= 0 ,0
Exp/Cntr=0.3,0.1

Type RM Length L Ch R = 1 ,16638.6 ,564.2,540.7,517.2
XS GIS Cut Line= 2
     2096150.182      413413.178     2096610.167      413781.805
#Sta/Elev= 30
       0 2751.68      20 2744.88    69.9  2727.4    79.9 2723.99    89.9 2720.69
   109.9 2714.37   119.9 2711.28   129.9 2708.37   139.9 2705.91   149.9 2703.89
   189.8 2696.46   209.8 2693.04   269.8  2683.7   286.1 2680.72   289.7 2680.04
   299.7 2678.82   309.7 2679.19   316.12680.323   319.7 2680.96   339.7 2686.11
   359.7 2690.96   379.7 2696.25   389.6 2699.04   449.6 2716.29   459.6 2719.34
   479.6 2726.17   489.6 2729.31   509.5 2735.24   549.5 2746.63   589.5 2757.62
#Mann= 3 , 0 , 0
       0      .1       0   286.1    .045       0   316.1      .1       0
Bank Sta=286.1,316.1
XS Rating Curve= 0 ,0
Exp/Cntr=0.3,0.1

Type RM Length L Ch R = 1 ,16097.9 ,270.2,271.5,272.8
XS GIS Cut Line= 2
     2095763.929      414132.186     2096678.392      413798.279
#Sta/Elev= 30
       0 2802.24    70.2 2781.88    80.3 2778.65    90.3 2774.72   110.4 2765.61
   130.5 2754.79   150.5 2743.36   160.6 2737.89   170.6 2732.97   180.6  2728.9
   250.9 2704.91   301.1 2684.44   321.2 2675.33   326.6  2673.5   331.2 2671.94
   341.2 2670.93   356.62671.841   431.6 2678.02   461.7 2679.94   501.8 2681.45
   592.1 2683.67   602.2 2684.39   612.2 2685.84   642.3 2692.36   702.5 2704.25
   742.7 2713.32   752.7 2715.99   782.8 2725.57   873.2 2750.39   973.5 2779.99
#Mann= 3 , 0 , 0
       0      .1       0   326.6    .045       0   356.6      .1       0
Bank Sta=326.6,356.6
XS Rating Curve= 0 ,0
Exp/Cntr=0.3,0.1

Type RM Length L Ch R = 1 ,15826.4 ,232.4,231,229.6
XS GIS Cut Line= 2
     2095916.882      414345.015     2096849.393      414065.441
#Sta/Elev= 30
       0 2721.42      10  2718.3    20.1 2715.99   100.4 2701.68   150.5  2691.9
   190.7 2683.55   200.7 2681.86   230.8 2678.73   240.9 2677.34   250.9 2675.36
   277.5 2668.99     281 2668.15     291 2666.64   301.1 2666.38   307.52666.738
   361.3 2671.62     542 2689.23   582.1  2694.5   602.2 2698.67   622.2 2703.94
   632.3 2707.02   642.3 2710.54   652.4  2714.5   682.5 2728.06   692.5 2732.07
   702.5 2735.56   792.9 2763.98   893.2 2797.49   953.4 2816.78   973.5 2822.91
#Mann= 3 , 0 , 0
       0      .1       0   277.5    .045       0   307.5      .1       0
Bank Sta=277.5,307.5
XS Rating Curve= 0 ,0
Exp/Cntr=0.3,0.1

Type RM Length L Ch R = 1 ,15595.4 ,237.7,264.8,291.9
XS GIS Cut Line= 3
     2095933.303       414375.33     2096152.436      414523.403
     2096727.395      414311.524
#Sta/Elev= 30
       0 2713.47    29.4 2708.38   146.9 2689.88   235.1 2675.54   244.9 2674.02
   264.5 2671.49   274.5 2671.02   284.6 2670.99   324.7  2671.9   344.8 2672.09
   354.9 2671.63   364.9  2670.5     375    2669     3932665.782   395.1  2665.4
   405.1 2664.36   415.2 2664.95     4232666.345   435.2 2668.55   445.3  2670.1
   545.7 2684.47     606 2693.67   646.2 2700.31   706.5 2711.16   716.5 2713.26
   726.6 2715.98   766.7 2727.91   796.9  2736.3   847.1 2749.82   877.2 2758.37
#Mann= 3 , 0 , 0
       0      .1       0     393    .045       0     423      .1       0
#XS Ineff= 2 , 0
          343.67 2674.87
Permanent Ineff=
       F       F
Bank Sta=393,423
XS Rating Curve= 0 ,0
Exp/Cntr=0.3,0.1

Type RM Length L Ch R = 1 ,15330.6 ,674.5,678,681.6
XS GIS Cut Line= 2
     2095909.644       414387.16      2096670.69      415018.079
#Sta/Elev= 30
       0    2719    10.1 2715.35    20.2 2712.84    30.3 2711.05   151.3 2691.34
   252.2 2674.22   282.4 2669.81   292.5 2668.77   302.6 2668.31   373.2 2669.38
   433.8 2670.82   453.9  2670.5   474.1 2668.28   524.82659.606   534.6 2658.81
   544.7 2659.08   554.8 2660.59     575  2666.1   605.2 2675.96   625.4 2683.62
   665.8 2700.96   685.9 2708.63   786.8 2744.52   877.6  2775.3   897.8 2781.42
     918 2786.45   958.3 2798.16   968.4 2799.78   978.5 2800.38   988.6 2800.42
#Mann= 3 , 0 , 0
       0      .1       0   524.8    .045       0   554.8      .1       0
Bank Sta=524.8,554.8
XS Rating Curve= 0 ,0
Exp/Cntr=0.3,0.1

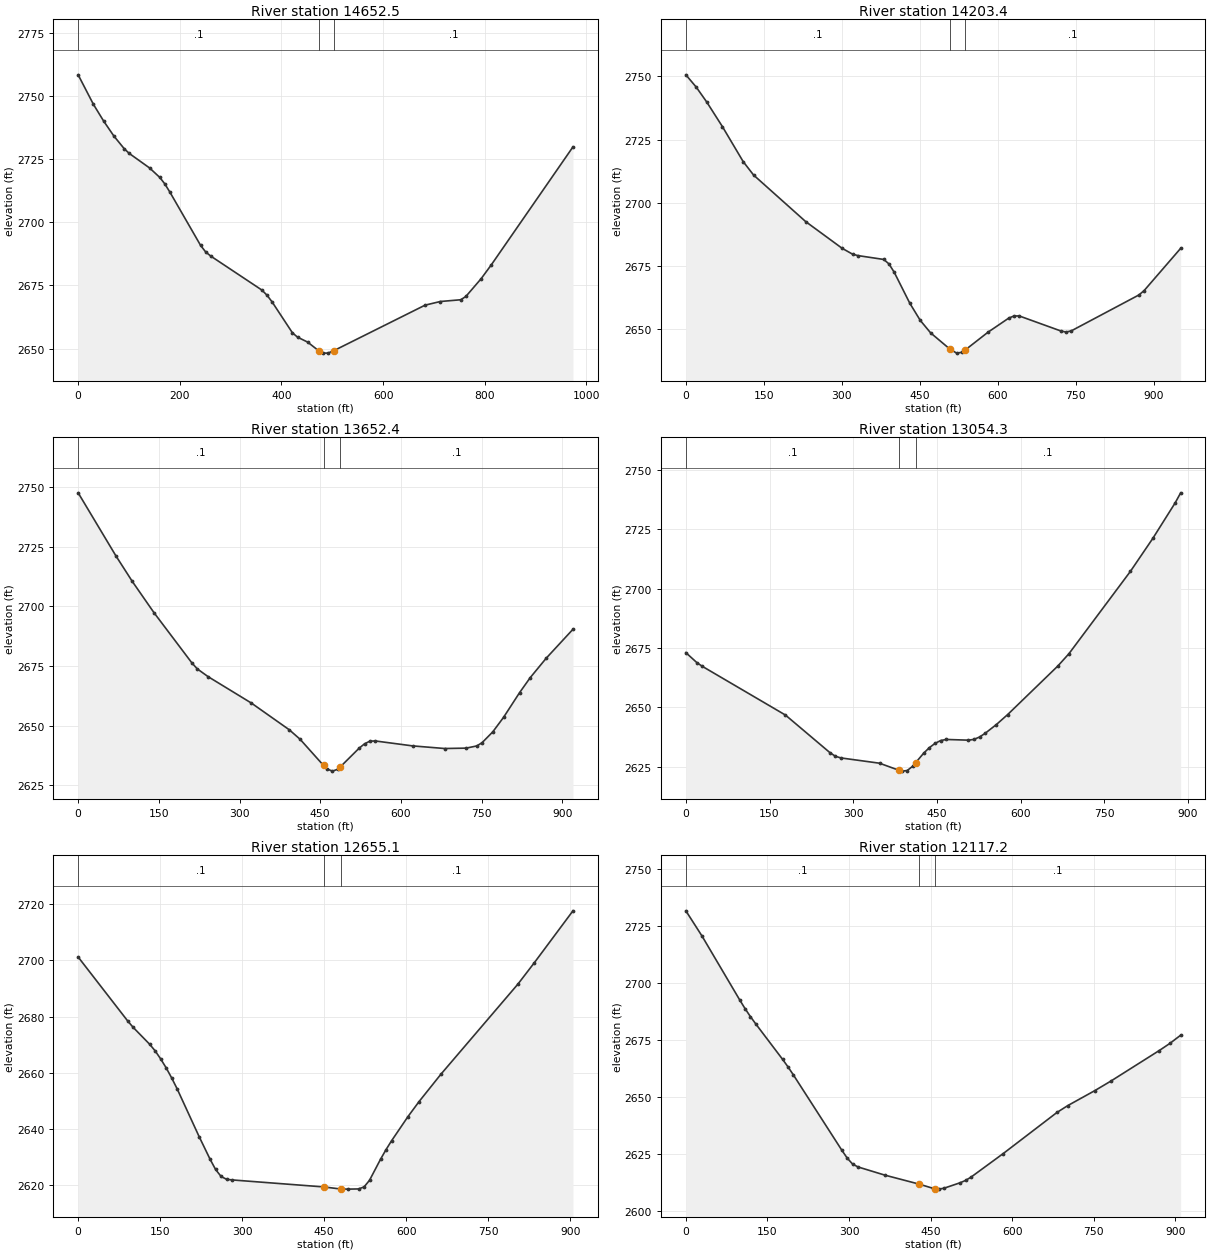
Type RM Length L Ch R = 1 ,14652.5 ,458.1,449.1,440.1
XS GIS Cut Line= 2
     2095439.556      414535.815      2096033.15      415307.426
#Sta/Elev= 30
       0 2758.32    30.1 2746.61    50.2 2740.01    70.2 2734.12    90.3 2729.16
   100.4 2727.23   140.5 2721.47   160.6 2717.72   170.6 2715.13   180.6 2711.87
   240.9 2690.82   250.9 2688.22   260.9 2686.59   361.3 2673.17   371.3 2671.17
   381.4 2668.51   421.5 2656.25   431.6 2654.51   451.6 2652.54   473.12649.144
   481.7 2648.19   491.8  2648.2   503.12649.171   682.5 2667.17   712.6 2668.62
   752.7 2669.31   762.8 2670.61   792.9 2677.66   812.9 2683.14   973.5  2729.8
#Mann= 3 , 0 , 0
       0      .1       0   473.1    .045       0   503.1      .1       0
Bank Sta=473.1,503.1
XS Rating Curve= 0 ,0
Exp/Cntr=0.3,0.1

Type RM Length L Ch R = 1 ,14203.4 ,563.9,551,538.3
XS GIS Cut Line= 2
     2094931.175      414939.756     2095758.798      415410.777
#Sta/Elev= 30
       0 2750.54      20 2745.67    40.1 2739.82    70.2 2730.13   110.3 2716.27
   130.3 2710.97   230.6 2692.58   300.7 2682.04   320.8 2679.72   330.8 2679.17
   380.9 2677.63   390.9 2675.86     401 2672.57     431 2660.33   451.1 2653.57
   471.1 2648.63   507.72642.302   521.2 2640.64   531.3 2640.98   537.72641.895
   581.4 2648.89   621.5 2654.48   631.5 2655.31   641.5 2655.33   721.7 2649.39
   731.8 2648.97   741.8 2649.43   872.1 2663.63   882.1 2665.37   952.3 2682.03
#Mann= 3 , 0 , 0
       0      .1       0   507.7    .045       0   537.7      .1       0
Bank Sta=507.7,537.7
XS Rating Curve= 0 ,0
Exp/Cntr=0.3,0.1

Type RM Length L Ch R = 1 ,13652.4 ,596.2,598.1,599.7
XS GIS Cut Line= 3
     2094856.658      415767.474     2095307.326      415722.853
     2095773.931      415702.207
#Sta/Elev= 30
       0 2747.75    70.4 2721.19   100.6 2710.55   140.9 2697.43   211.3 2676.34
   221.4  2673.8   241.5 2670.54     322 2659.44   392.5 2648.21   412.6 2644.23
   456.2 2633.22   462.8 2631.72   472.8 2630.84   482.7 2631.63   486.22632.365
   522.4 2640.48   532.4 2642.31   542.3 2643.42   552.2 2643.52   621.8 2641.44
   681.4 2640.34   721.2  2640.5   741.1 2641.42     751  2642.8   770.9 2647.35
   790.8 2653.41   820.6 2663.79   840.4  2670.1   870.2 2678.28   919.9 2690.43
#Mann= 3 , 0 , 0
       0      .1       0   456.2    .045       0   486.2      .1       0
Bank Sta=456.2,486.2
XS Rating Curve= 0 ,0
Exp/Cntr=0.3,0.1

Type RM Length L Ch R = 1 ,13054.3 ,391.1,399.2,407.3
XS GIS Cut Line= 3
     2095055.455      416295.371     2095491.847      416306.152
     2095941.151        416341.8
#Sta/Elev= 30
       0 2673.07    19.8 2668.84    29.8 2667.25   178.6 2646.75     258 2630.98
   267.9 2629.41   277.8  2628.7   347.2 2626.47     3822623.496   386.9 2623.13
   396.8 2623.37   406.8 2625.21     4122626.691   426.6 2630.76   436.5    2633
   446.5 2634.78   456.6 2635.99   466.6 2636.48   506.6 2636.18   516.6  2636.5
   526.7 2637.53   536.7 2639.08   556.7 2642.75   576.8 2646.93   666.9 2667.42
   686.9 2672.63   797.1 2707.33   837.2  2721.2   877.2 2736.14   887.2 2740.42
#Mann= 3 , 0 , 0
       0      .1       0     382    .045       0     412      .1       0
Bank Sta=382,412
XS Rating Curve= 0 ,0
Exp/Cntr=0.3,0.1

Type RM Length L Ch R = 1 ,12655.1 ,535.7,537.9,540.2
XS GIS Cut Line= 3
     2094995.433      416528.504     2095415.918      416695.657
     2095837.775       416859.25
#Sta/Elev= 30
       0 2701.19    90.5 2678.49   100.6 2676.19   130.7  2670.2   140.8 2667.84
   150.8 2665.01   160.9 2661.82   170.9 2658.26     181 2654.36   221.2 2637.38
   241.3 2629.31   251.4 2625.67   261.4 2623.19   271.5 2622.18   281.6 2621.96
     4502619.457     4802618.733   492.7 2618.69   512.8 2618.76   522.9 2619.47
   532.9 2621.83     553 2629.29   563.1 2632.73   573.2 2635.87   603.3 2644.49
   623.4 2649.78   663.6 2659.56   804.4 2691.58   834.6 2699.23     905 2717.61
#Mann= 3 , 0 , 0
       0      .1       0     450    .045       0     480      .1       0
Bank Sta=450,480
XS Rating Curve= 0 ,0
Exp/Cntr=0.3,0.1

Type RM Length L Ch R = 1 ,12117.2 ,527.4,526.6,525.8
XS GIS Cut Line= 3
     2094758.846      416960.527     2095163.846      417167.936
     2095570.559      417371.912
#Sta/Elev= 30
       0 2731.52    29.7 2720.46    98.9 2692.51   108.8 2688.68   118.7 2685.16
   128.6 2681.94     178 2666.39   187.9  2663.1   197.8 2659.58   286.9 2626.57
   296.8 2623.12   306.6 2620.54   316.5 2619.28     366 2615.68   428.8 2611.76
     455 2609.87   458.82609.747   464.9 2609.55   474.8 2609.95   504.5 2612.35
   514.4 2613.37   524.3 2614.79   583.6 2625.13   682.5 2643.16   702.3 2646.15
   751.8 2652.68   781.4 2656.87   870.4 2670.26   890.2 2673.42     910 2677.02
#Mann= 3 , 0 , 0
       0      .1       0   428.8    .045       0   458.8      .1       0
Bank Sta=428.8,458.8
XS Rating Curve= 0 ,0
Exp/Cntr=0.3,0.1

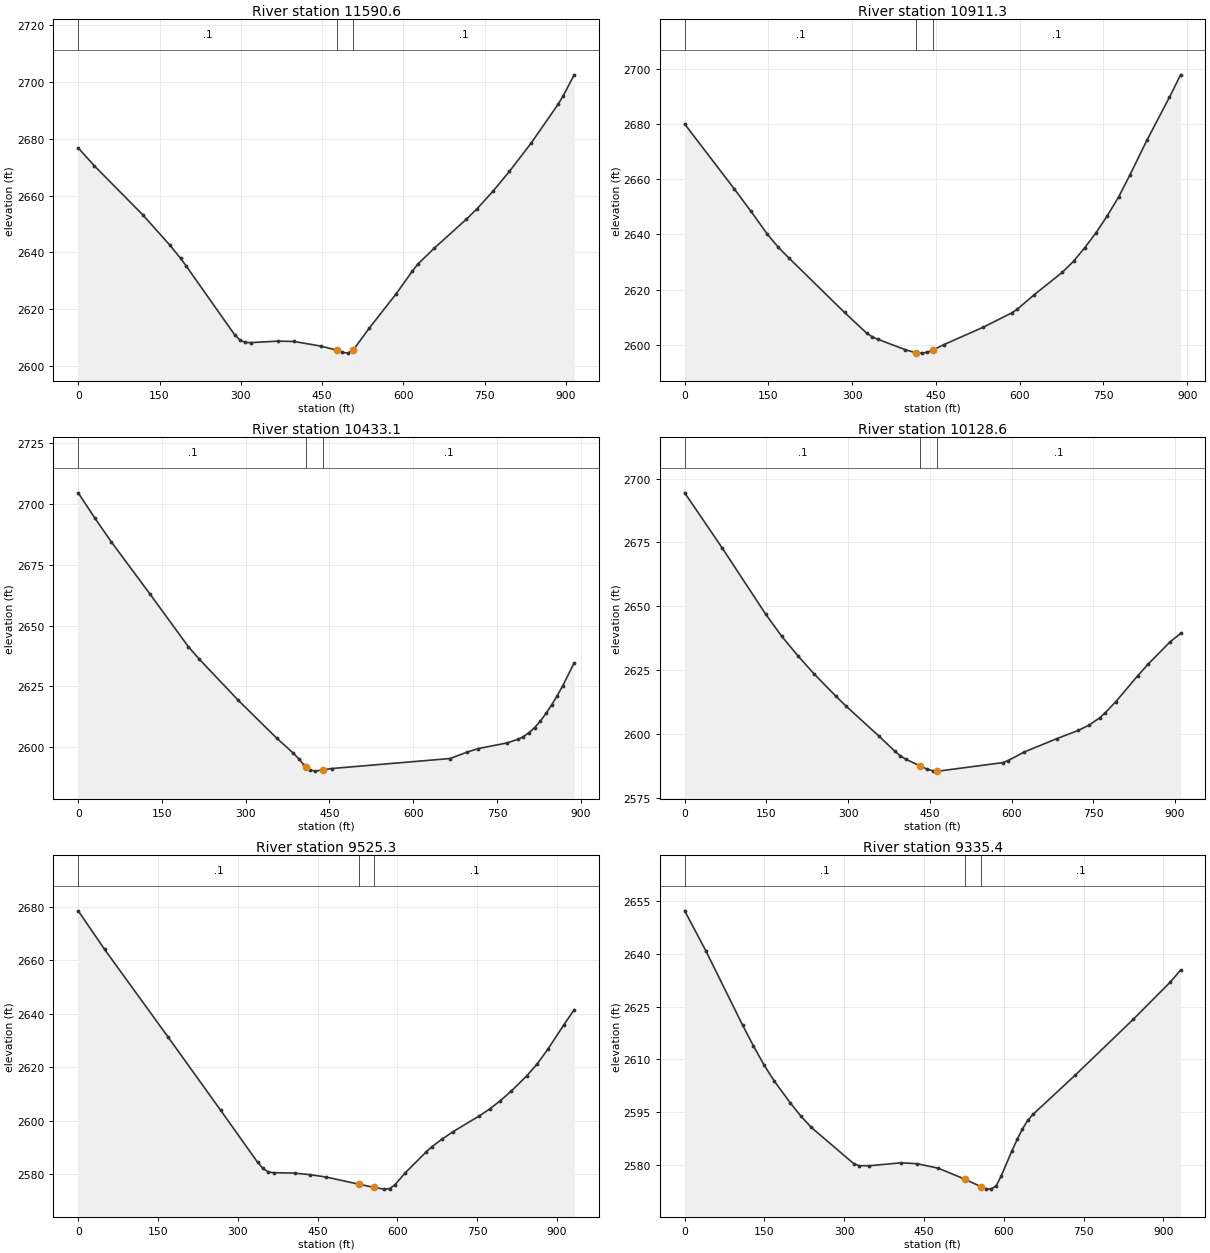
Type RM Length L Ch R = 1 ,11590.6 ,670.9,679.3,687.2
XS GIS Cut Line= 3
     2094534.764       417443.46     2094947.858      417640.194
     2095362.576      417833.429
#Sta/Elev= 30
       0 2676.78    29.8 2670.48   119.4 2653.17   169.1 2642.55     189 2637.88
   198.9  2635.3   288.4 2611.05   298.4 2609.11   308.4 2608.28   318.3 2608.21
     368 2608.73   397.9 2608.62   447.6 2606.99     4772605.584   487.4 2604.82
   497.3 2604.51     507 2605.49   537.1 2613.33   586.8 2625.43   616.7 2633.44
   626.6 2635.85   656.5 2641.38   716.2 2651.67     736 2655.37   765.9 2661.66
   795.7 2668.54   835.5 2678.41   885.2 2692.08   895.2 2695.23   915.1 2702.53
#Mann= 3 , 0 , 0
       0      .1       0     477    .045       0     507      .1       0
Bank Sta=477,507
XS Rating Curve= 0 ,0
Exp/Cntr=0.3,0.1

Type RM Length L Ch R = 1 ,10911.3 ,479.3,478.2,477.6
XS GIS Cut Line= 3
     2094236.445      417768.105     2094528.272      418103.139
     2094831.953       418426.86
#Sta/Elev= 30
       0 2679.98    88.9 2656.48   118.5 2648.44   148.1 2640.09   167.8 2635.34
   187.6  2631.3   286.3 2611.77   325.8  2604.3   335.7 2602.99   345.6 2602.09
   394.9  2598.3   414.52597.139   424.6 2597.04   434.4 2597.34   444.52598.141
   464.5 2600.14   535.1 2606.46   585.5 2611.58   595.6 2612.94   625.9 2618.16
   676.3  2626.3   696.5 2630.32   716.7 2635.24   736.9 2640.68     757  2646.8
   777.2 2653.59   797.4 2661.54   827.6 2674.04     868  2689.6   888.2 2697.79
#Mann= 3 , 0 , 0
       0      .1       0   414.5    .045       0   444.5      .1       0
Bank Sta=414.5,444.5
XS Rating Curve= 0 ,0
Exp/Cntr=0.3,0.1

Type RM Length L Ch R = 1 ,10433.1 ,301.8,304.4,306.5
XS GIS Cut Line= 3
     2093807.754      418033.302     2094128.684      418340.571
     2094460.396      418635.502
#Sta/Elev= 30
       0 2704.62    29.6 2694.31    59.2 2684.48   128.4 2663.04   197.5 2641.28
   217.2 2636.14   286.3 2619.41   355.4 2603.77   385.1 2597.62   394.9 2595.29
   404.8 2592.56   408.62591.846   414.7  2590.7   424.6 2590.19   438.62590.767
   454.4 2591.27   666.2 2595.38   696.5 2598.01   716.7 2599.48   767.1 2601.73
   787.3 2603.25   797.4  2604.4   807.5 2606.02   817.6 2608.12   827.6 2610.75
   837.7 2613.89   847.8  2617.4   857.9 2621.22     868 2625.38   888.2 2634.69
#Mann= 3 , 0 , 0
       0      .1       0   408.6    .045       0   438.6      .1       0
Bank Sta=408.6,438.6
XS Rating Curve= 0 ,0
Exp/Cntr=0.3,0.1

Type RM Length L Ch R = 1 ,10128.6 ,604.3,603.4,603
XS GIS Cut Line= 3
     2093658.166      418232.386     2093949.473      418582.397
     2094253.193      418921.098
#Sta/Elev= 30
       0 2694.41    69.3 2672.69   148.5 2646.94   178.2 2638.21   207.9 2630.58
   237.6 2623.48   277.2 2614.84     297 2610.74   356.4 2599.16   386.1 2593.15
     396 2591.35   405.9  2590.1   432.8 2587.36   445.5 2586.15   455.3 2585.56
   462.82585.448   465.3 2585.41   583.9 2588.74   593.8 2589.57   623.5 2592.93
   682.8 2598.11   722.4 2601.35   742.2 2603.42     762 2606.33   771.8 2608.25
   791.6 2612.67   831.2 2622.69     851 2627.38   890.5 2635.96   910.3 2639.34
#Mann= 3 , 0 , 0
       0      .1       0   432.8    .045       0   462.8      .1       0
Bank Sta=432.8,462.8
XS Rating Curve= 0 ,0
Exp/Cntr=0.3,0.1

Type RM Length L Ch R = 1 ,9525.3  ,190,190,189.9
XS GIS Cut Line= 3
      2093228.54      418639.868     2093526.926      418998.386
     2093838.035      419345.326
#Sta/Elev= 30
       0 2678.46    49.6 2664.04   168.7 2631.32     268  2603.8   337.4 2584.36
   347.4 2582.09   357.3  2580.8   367.2 2580.51   406.9 2580.35   436.7 2579.75
   466.4 2578.87     527 2576.23     5572574.984   575.5 2574.36   585.4 2574.56
   595.3 2575.96   615.2 2580.53   654.8  2588.4   664.7  2590.2   684.6 2593.14
   704.4 2595.81     754 2601.75   773.8 2604.37   793.6 2607.43   813.5 2610.91
   843.2 2616.72     863 2621.22   882.9 2626.68   912.6 2635.69   932.4 2641.47
#Mann= 3 , 0 , 0
       0      .1       0     527    .045       0     557      .1       0
Bank Sta=527,557
XS Rating Curve= 0 ,0
Exp/Cntr=0.3,0.1

Type RM Length L Ch R = 1 ,9335.4  ,485.8,496.3,506.7
XS GIS Cut Line= 3
     2093089.105      418766.327     2093387.491      419124.844
       2093698.6      419471.785
#Sta/Elev= 30
       0 2652.25    39.7 2640.89   109.2 2619.61     129 2613.86   148.9 2608.44
   168.7 2603.72   198.5 2597.57   218.3 2593.83   238.2 2590.56   317.6 2580.29
   327.5 2579.68   347.4 2579.66   406.9  2580.5   436.7 2580.24   476.4 2578.98
   526.92575.832   556.92573.696   565.6 2573.16   575.5    2573   585.4 2573.88
   595.3 2576.79   615.2 2583.91   625.1 2587.14     635 2590.13   644.9 2592.56
   654.8 2594.28   734.2 2605.46   843.2 2621.33   912.6  2631.9   932.4 2635.39
#Mann= 3 , 0 , 0
       0      .1       0   526.9    .045       0   556.9      .1       0
Bank Sta=526.9,556.9
XS Rating Curve= 0 ,0
Exp/Cntr=0.3,0.1

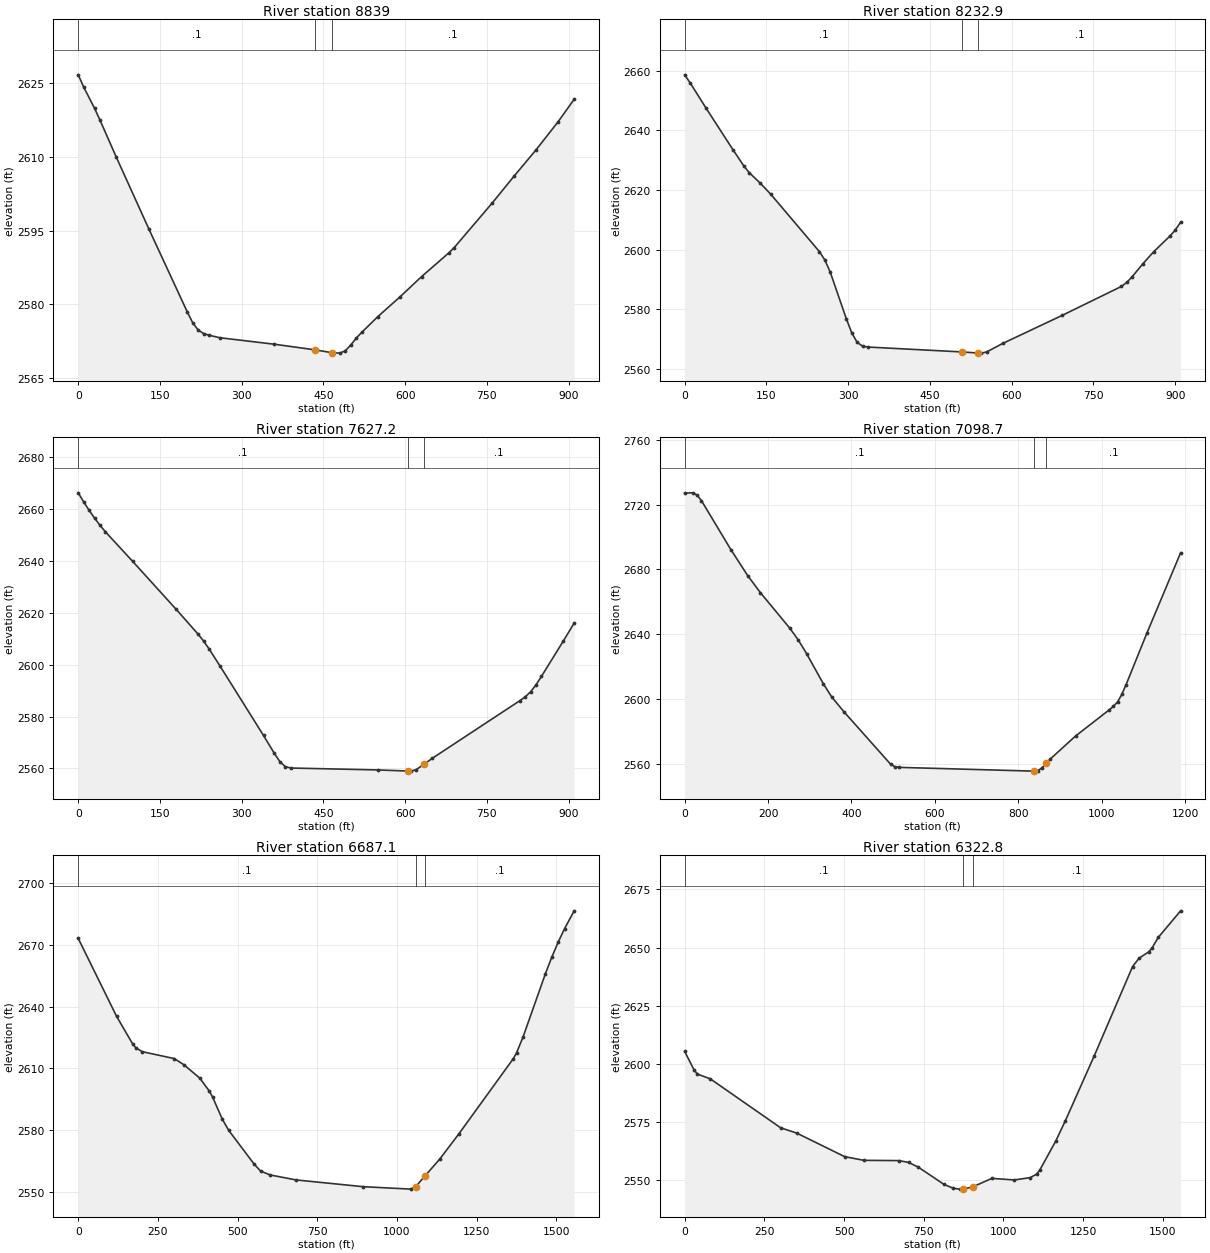
Type RM Length L Ch R = 1 ,8839    ,603.6,606.1,608.6
XS GIS Cut Line= 2
     2092857.696      418926.215     2093101.714      419802.888
#Sta/Elev= 30
       0 2626.71      10 2624.23      30  2619.9      40 2617.48      70 2609.94
     130 2595.27     200 2578.51     210  2576.3     220 2574.81     230 2574.09
     240 2573.74     260 2573.23     360 2571.91     435 2570.76     465  2570.2
     480  2570.1     490 2570.57     500 2571.73     510 2573.13     520  2574.3
     550 2577.55     590  2581.5     630 2585.66     680 2590.49     690 2591.58
     760 2600.68     800 2606.13     840 2611.44     880 2617.08     910 2621.74
#Mann= 3 , 0 , 0
       0      .1       0     435    .045       0     465      .1       0
Bank Sta=435,465
XS Rating Curve= 0 ,0
Exp/Cntr=0.3,0.1

Type RM Length L Ch R = 1 ,8232.9  ,605.4,605.7,606.1
XS GIS Cut Line= 3
     2092299.101      418955.354     2092373.216      419404.277
     2092447.332        419853.2
#Sta/Elev= 30
       0 2658.64     9.9 2655.98    39.6 2647.37      89 2633.42   108.8 2628.03
   118.7  2625.8   138.5 2622.36   158.3 2618.54   247.3 2599.36   257.2 2596.57
   267.1 2592.49   296.7 2576.82   306.6 2572.13   316.5 2568.96   326.4 2567.69
   336.3 2567.39     5092565.749     539 2565.37     544 2565.35   553.9 2565.73
   583.6  2568.6   692.4 2577.98   801.2 2587.69   811.1 2589.03     821 2590.95
   840.8 2595.32   860.5 2599.32   890.2 2604.56   900.1 2606.59     910 2609.25
#Mann= 3 , 0 , 0
       0      .1       0     509    .045       0     539      .1       0
Bank Sta=509,539
XS Rating Curve= 0 ,0
Exp/Cntr=0.3,0.1

Type RM Length L Ch R = 1 ,7627.2  ,531.1,528.5,525.9
XS GIS Cut Line= 2
     2091687.778      418883.896     2091836.009      419781.742
#Sta/Elev= 30
       0 2666.36      10 2662.86      20 2659.63      30 2656.61      40 2653.82
      50  2651.3     100  2639.9     180 2621.35     220 2611.82     230 2609.19
     240 2606.18     260  2599.6     340 2572.74     360 2565.79     370 2562.66
     380 2560.72     390 2560.18     550 2559.44   604.72559.012     610 2558.98
     620 2559.52   634.72561.631     650 2563.97     810 2586.11     820 2587.61
     830 2589.57     840 2592.27     850 2595.54     890 2609.13     910 2616.11
#Mann= 3 , 0 , 0
       0      .1       0   604.7    .045       0   634.7      .1       0
Bank Sta=604.7,634.7
XS Rating Curve= 0 ,0
Exp/Cntr=0.3,0.1

Type RM Length L Ch R = 1 ,7098.7  ,413.1,411.6,411.5
XS GIS Cut Line= 2
     2091092.426      418911.943     2091406.783      420059.072
#Sta/Elev= 30
       0 2727.11    20.2 2727.21    30.2 2725.66    40.3 2722.36   110.9  2692.2
   151.2 2676.22   181.4  2665.8     252  2643.9   272.2  2636.7   292.3 2628.25
   332.6 2609.62   352.8 2601.45     383  2592.1   493.9 2560.11     504 2558.55
   514.1 2558.17   836.6 2555.85   837.42555.876   846.7 2556.18   856.8  2557.8
   867.42560.679     877 2563.35   937.4 2577.47  1018.1 2593.55  1028.1 2595.68
  1038.2 2598.48  1048.3 2603.04  1058.4 2608.96  1108.8    2641  1189.4  2690.3
#Mann= 3 , 0 , 0
       0      .1       0   837.4    .045       0   867.4      .1       0
Bank Sta=837.4,867.4
XS Rating Curve= 0 ,0
Exp/Cntr=0.3,0.1

Type RM Length L Ch R = 1 ,6687.1  ,365.7,364.3,361.3
XS GIS Cut Line= 2
     2090652.023      418801.754      2091056.78      420303.873
#Sta/Elev= 30
       0 2673.08   120.4 2635.22   170.6 2621.89   180.7 2619.98   200.7 2618.09
   301.1 2614.74   331.2 2611.78   381.4 2605.24   411.5  2598.9   421.5 2596.08
   451.6 2585.45   471.7 2579.98     552  2563.5   572.1 2560.14   602.2 2558.26
   682.5 2555.86   893.3 2552.57  1043.8 2551.38  1058.82552.621  1088.82557.965
  1134.2 2565.98  1194.4 2578.27    1365 2614.73    1375 2617.53  1395.1 2625.08
  1465.4 2655.87  1485.4  2663.9  1505.5  2671.2  1525.6 2677.77  1555.7 2686.44
#Mann= 3 , 0 , 0
       0      .1       0  1058.8    .045       0  1088.8      .1       0
Bank Sta=1058.8,1088.8
XS Rating Curve= 0 ,0
Exp/Cntr=0.3,0.1

Type RM Length L Ch R = 1 ,6322.8  ,426.6,428.5,430.5
XS GIS Cut Line= 2
      2090245.48      418934.279     2090837.043      420373.112
#Sta/Elev= 30
       0 2605.27    30.1 2597.16    40.2 2595.52    80.3 2593.49   301.1 2572.42
   351.3 2570.15   501.8 2560.01   562.1 2558.42   672.5  2558.3   702.6 2557.51
   732.7  2555.5     813 2548.11   843.1 2546.37   863.2 2546.03   873.32546.041
   903.3 2546.98   963.5 2550.65  1033.8 2549.98    1084 2550.98    1104  2552.5
  1114.1 2554.26  1164.3  2566.8  1194.4 2575.52  1284.7 2603.36  1405.1 2641.82
  1425.2 2645.38  1455.3 2648.09  1465.4 2649.67  1485.4 2654.32  1555.7 2665.78
#Mann= 3 , 0 , 0
       0      .1       0   873.3    .045       0   903.3      .1       0
Bank Sta=873.3,903.3
XS Rating Curve= 0 ,0
Exp/Cntr=0.3,0.1