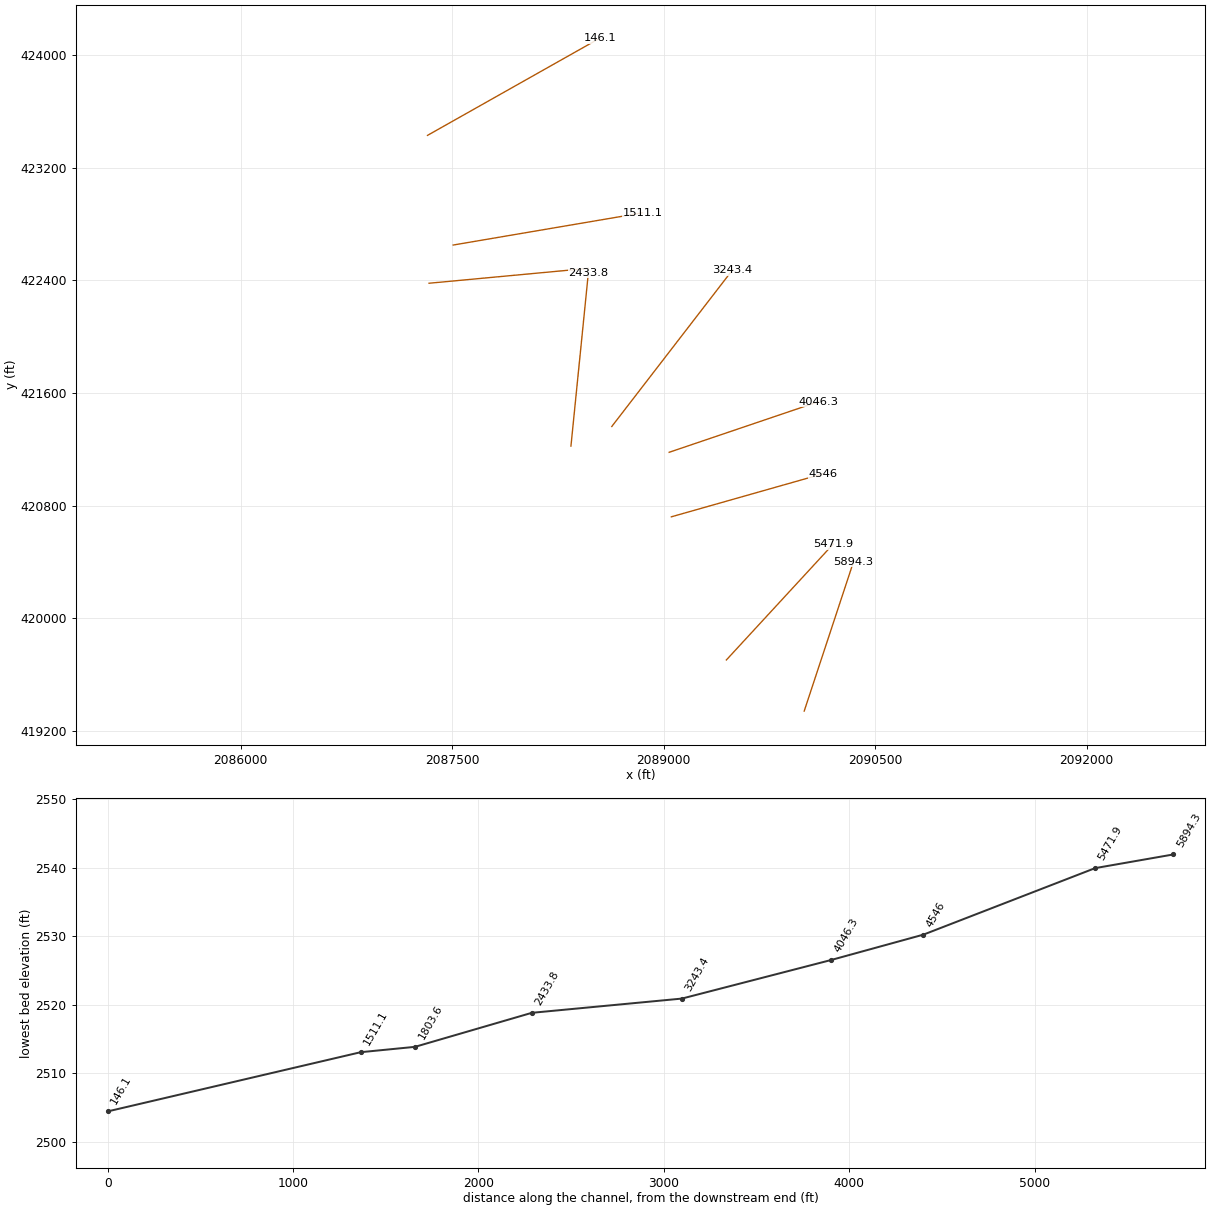
HEC-RAS study LaurCk.prj: LaurCk

--- LaurCk.g01 (geometry) --- (continued)

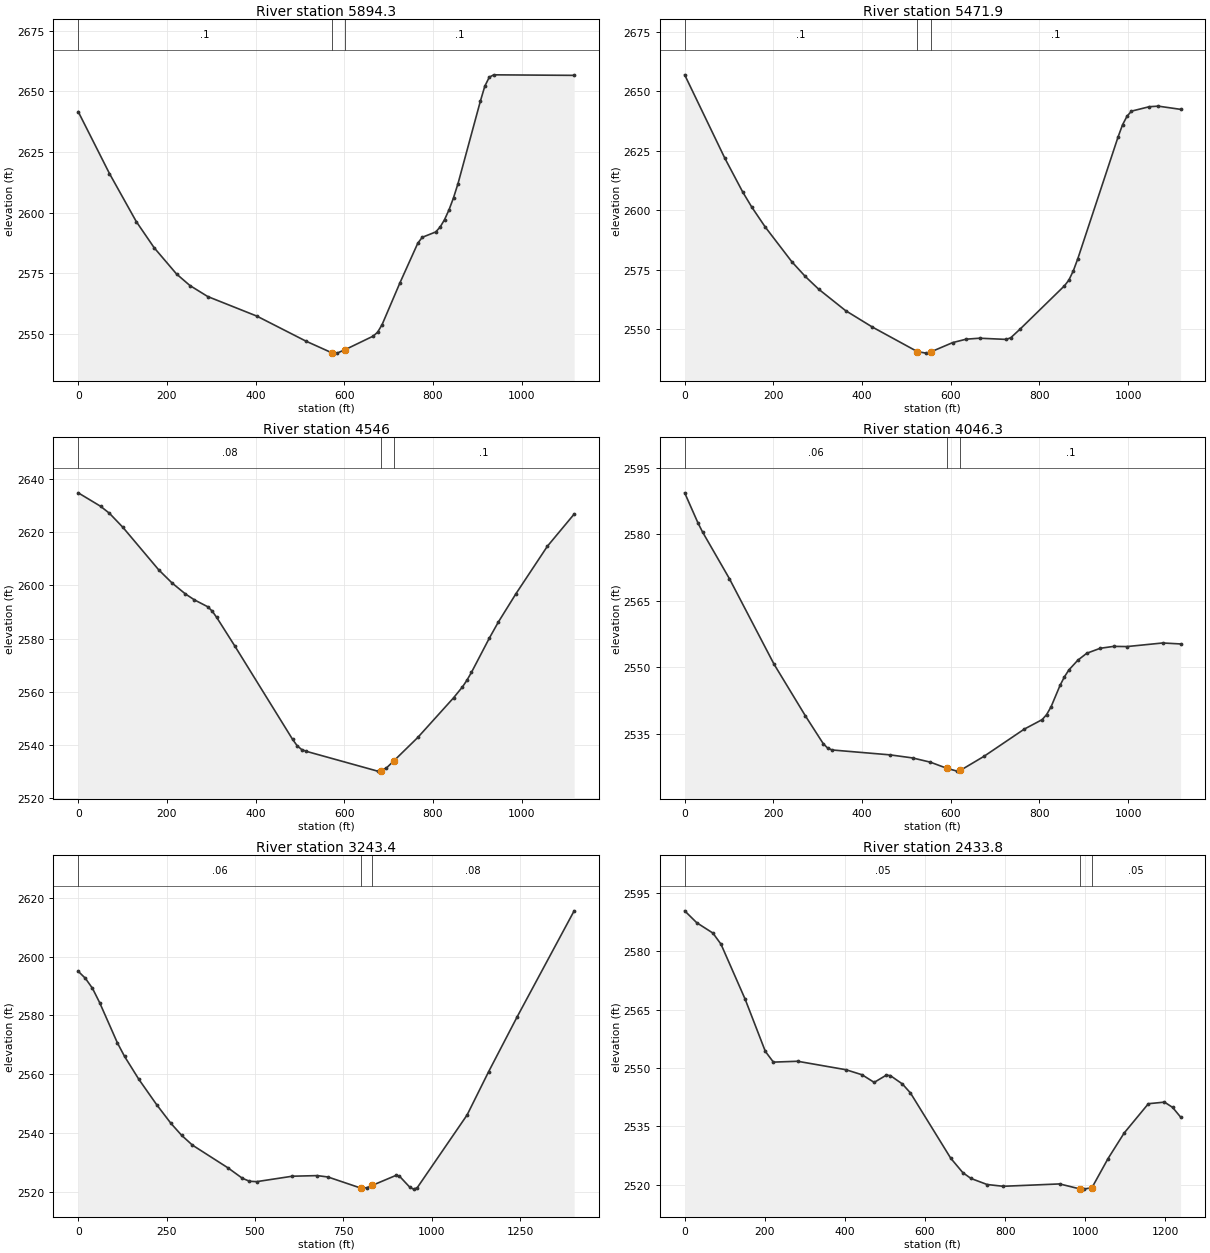
Type RM Length L Ch R = 1 ,5894.3  ,432.5,422.5,412.5
XS GIS Cut Line= 2
     2089996.794      419340.814      2090346.85      420403.062
#Sta/Elev= 30
       0 2641.67    70.5  2616.1     131 2596.26   171.3 2585.46   221.7 2574.63
   251.9 2569.86   292.2  2565.3     403 2557.22   513.9 2546.86   572.62542.028
   574.3 2541.94   584.4 2541.99   602.62543.432     665 2548.95   675.1 2550.57
   685.2 2553.68   725.5 2570.96   765.8 2587.34   775.8 2589.77   806.1 2591.98
   816.2 2594.01   826.2 2597.11   836.3 2601.16   846.4 2606.13   856.5 2611.97
   906.8 2645.93   916.9 2652.18     927  2655.9   937.1 2656.88  1118.4 2656.66
#Mann= 3 , 0 , 0
       0      .1       0   572.6    .045       0   602.6      .1       0
Bank Sta=572.6,602.6
XS Rating Curve= 0 ,0
Exp/Cntr=0.3,0.1

Type RM Length L Ch R = 1 ,5471.9  ,938.2,925.8,913.2
XS GIS Cut Line= 2
     2089444.678      419703.679     2090202.065      420526.644
#Sta/Elev= 30
       0 2656.87    90.7 2621.79     131  2607.6   151.1 2601.36   181.4    2593
   241.8  2578.3     272 2572.15   302.3 2566.79   362.7 2557.82   423.2  2550.9
   524.62540.594   544.1 2539.94   554.6 2540.42   604.6 2544.38   634.8  2545.8
     665 2546.21   725.5  2545.7   735.6 2546.45   755.7 2549.91   856.5 2568.24
   866.5 2570.65   876.6 2574.61   886.7 2579.69   977.4  2630.8   987.4 2635.87
   997.5 2639.47  1007.6 2641.61  1047.9 2643.48  1068.1 2643.71  1118.4 2642.36
#Mann= 3 , 0 , 0
       0      .1       0   524.6    .045       0   554.6      .1       0
Bank Sta=524.6,554.6
XS Rating Curve= 0 ,0
Exp/Cntr=0.3,0.1

Type RM Length L Ch R = 1 ,4546    ,499.5,499.8,500.2
XS GIS Cut Line= 2
     2089054.387      420720.808     2090130.218      421026.578
#Sta/Elev= 30
       0 2634.79    50.4 2629.74    70.5 2627.09   100.8 2621.82   181.4 2605.88
   211.6 2600.92   241.8 2596.79     262 2594.58   292.2 2591.98   302.3 2590.32
   312.4 2587.95   352.7 2577.36   483.6 2542.12   493.7 2539.78   503.8 2538.35
   513.9 2537.69   675.1 2530.23   682.42530.367   695.2 2531.43   712.42534.187
   765.8 2542.88   846.4 2557.76   866.5 2561.87   876.6 2564.38   886.7  2567.3
     927 2580.16   947.2 2586.17   987.4 2596.95    1058 2614.71  1118.4  2626.8
#Mann= 3 , 0 , 0
       0     .08       0   682.4    .045       0   712.4      .1       0
Bank Sta=682.4,712.4
XS Rating Curve= 0 ,0
Exp/Cntr=0.3,0.1

Type RM Length L Ch R = 1 ,4046.3  ,789.2,802.9,816.6
XS GIS Cut Line= 2
     2089038.911      421179.245     2090098.004       421538.73
#Sta/Elev= 30
       0 2589.38    30.2 2582.53    40.3 2580.53   100.8    2570   201.5 2550.67
     272 2539.03   312.4 2532.73   322.4 2531.72   332.5 2531.29   463.5 2530.18
   513.9 2529.49   554.2 2528.53   591.92527.121   614.4 2526.51   621.92526.692
   675.1 2529.86   765.8    2536   806.1 2538.14   816.2 2539.28   826.2 2541.03
   846.4 2545.86   856.5 2547.83   866.5 2549.38   886.7 2551.58   906.8 2553.14
   937.1 2554.26   967.3 2554.69   997.5 2554.65  1078.1 2555.46  1118.4 2555.24
#Mann= 3 , 0 , 0
       0     .06       0   591.9    .045       0   621.9      .1       0
Bank Sta=591.9,621.9
XS Rating Curve= 0 ,0
Exp/Cntr=0.3,0.1

Type RM Length L Ch R = 1 ,3243.4  ,796.5,809.5,822.6
XS GIS Cut Line= 2
     2088632.368      421362.872     2089488.227      422474.674
#Sta/Elev= 30
       0 2594.99    20.2 2592.61    40.4 2589.18    60.6 2584.33     111  2570.6
   131.2 2566.02   171.6 2558.23   222.1 2549.59   262.4 2543.25   292.7 2539.18
     323 2535.87     424  2528.1   464.3 2524.59   484.5 2523.57   504.7 2523.43
   605.6 2525.28   676.3 2525.49   706.6 2525.02   801.12521.181   817.6 2521.41
   831.12522.125   898.4 2525.53   908.5 2525.34   938.7 2521.47   948.8 2520.89
   958.9 2521.33  1100.2 2546.11  1160.8 2560.76  1241.6 2579.44  1403.1 2615.55
#Mann= 3 , 0 , 0
       0     .06       0   801.1    .045       0   831.1     .08       0
Bank Sta=801.1,831.1
XS Rating Curve= 0 ,0
Exp/Cntr=0.3,0.1

Type RM Length L Ch R = 1 ,2433.8  ,661.8,630.3,598.7
XS GIS Cut Line= 2
     2088342.547      421222.923     2088466.162      422454.647
#Sta/Elev= 30
       0 2590.46    30.2 2587.39    70.4 2584.74    90.6 2581.88     151 2567.69
   201.3 2554.28   221.4 2551.51   281.8 2551.73   402.6 2549.55   442.8 2548.25
     473 2546.29   503.2 2548.15   513.3 2548.04   543.5 2545.88   563.6 2543.56
   664.2 2526.75   694.4 2523.04   714.6 2521.56   754.8    2520   795.1 2519.54
     936 2520.15   986.72518.858   996.4 2518.81  1016.72519.207  1056.8 2526.69
    1097 2533.26  1157.4  2540.8  1197.6 2541.21  1217.8 2539.86  1237.9 2537.36
#Mann= 3 , 0 , 0
       0     .05       0   986.7    .045       0  1016.7     .05       0
Bank Sta=986.7,1016.7
XS Rating Curve= 0 ,0
Exp/Cntr=0.3,0.1

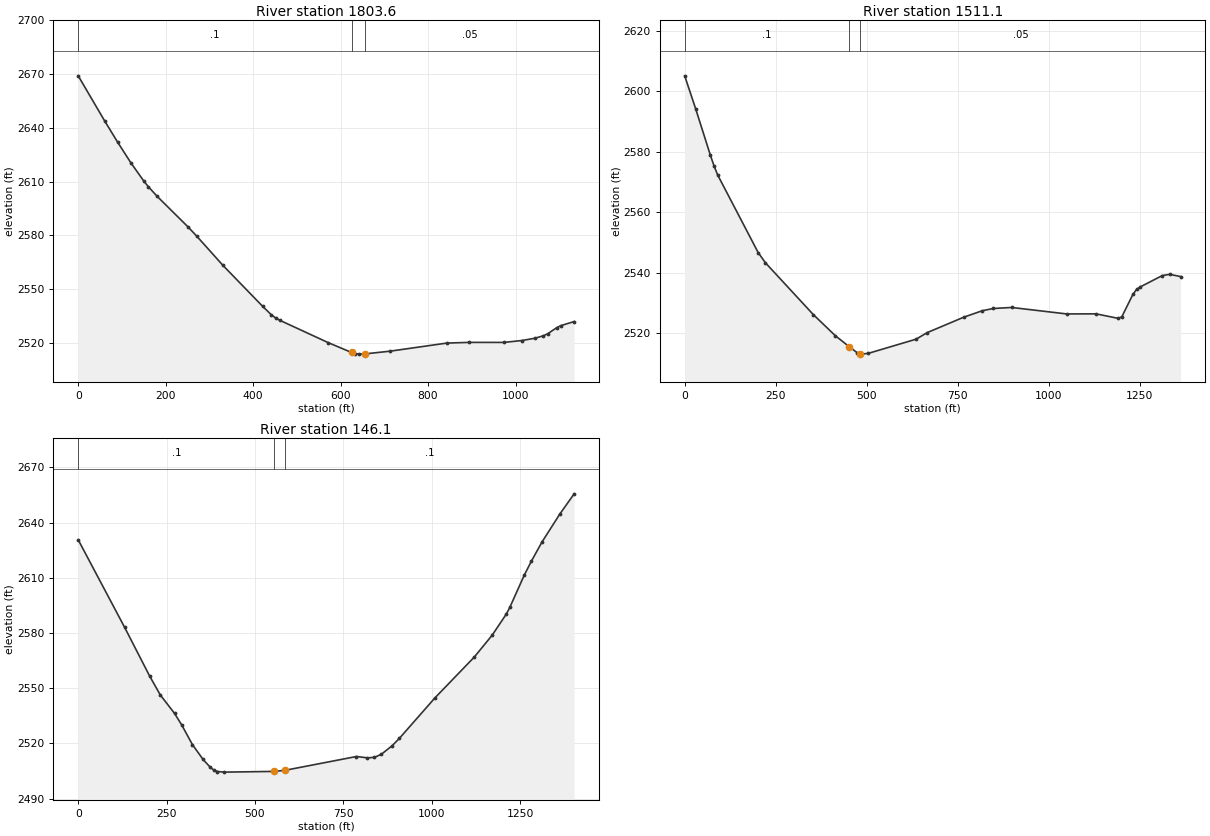
Type RM Length L Ch R = 1 ,1803.6  ,290.8,292.5,294.2
XS GIS Cut Line= 2
      2087336.28      422380.434     2088465.439      422486.141
#Sta/Elev= 30
       0 2669.01    60.2 2643.98    90.3 2631.97   120.4 2620.53   150.5 2610.15
   160.6 2607.14   180.6  2601.8   250.9 2584.83     271 2579.63   331.2 2563.26
   421.5 2540.55   441.6 2535.79   451.6 2533.96   461.7 2532.62   572.1  2520.2
   625.12514.769   632.3 2514.17   642.3 2513.84   655.12513.957   712.6 2515.47
     843    2520   893.2 2520.38   973.5 2520.37  1013.7 2521.41  1043.8 2522.66
  1063.8 2524.08  1073.9 2525.24    1094 2528.55    1104 2529.75  1134.1    2532
#Mann= 3 , 0 , 0
       0      .1       0   625.1    .045       0   655.1     .05       0
Bank Sta=625.1,655.1
XS Rating Curve= 0 ,0
Exp/Cntr=0.3,0.1

Type RM Length L Ch R = 1 ,1511.1  ,1357.4,1365,1372
XS GIS Cut Line= 2
     2087507.471      422651.838     2088850.384      422880.732
#Sta/Elev= 30
       0 2605.03    30.3 2594.09    70.6 2578.79    80.7 2575.24    90.8 2572.22
   201.8 2546.64     222 2543.22   353.2 2526.15   413.7 2519.16   452.72515.449
   474.3 2513.49   482.72513.132   484.4 2513.06   504.6 2513.32   635.7    2518
     666 2520.16   766.9 2525.28   817.4  2527.4   847.6 2528.14   898.1 2528.48
  1049.5 2526.34  1130.2 2526.37  1190.7 2524.88  1200.8  2525.4  1231.1 2532.77
  1241.2 2534.43  1251.3 2535.26  1311.8 2539.02    1332 2539.43  1362.3  2538.7
#Mann= 3 , 0 , 0
       0      .1       0   452.7    .045       0   482.7     .05       0
Bank Sta=452.7,482.7
XS Rating Curve= 0 ,0
Exp/Cntr=0.3,0.1

Type RM Length L Ch R = 1 ,146.1   ,154.6,146.1,137.5
XS GIS Cut Line= 2
     2087325.389      423431.047      2088546.93       424121.29
#Sta/Elev= 30
       0 2630.61   131.2 2583.11   201.9 2556.67   232.2 2546.34   272.5 2536.33
   292.7 2530.07     323  2519.4   353.3 2511.29   373.5 2507.07   383.6 2505.56
   393.7 2504.75   413.8 2504.41   555.2  2504.8   585.22505.402   787.3  2512.9
   817.6 2512.18   837.8  2512.4     858 2514.16   888.3 2518.78   908.5 2522.72
  1009.4 2544.78  1120.4 2566.89  1170.9 2578.73  1211.3 2590.31  1221.4 2594.05
  1261.8 2611.36  1281.9 2618.94  1312.2 2629.46  1362.7 2644.65  1403.1  2655.6
#Mann= 3 , 0 , 0
       0      .1       0   555.2    .045       0   585.2      .1       0
Bank Sta=555.2,585.2
XS Rating Curve= 0 ,0
Exp/Cntr=0.3,0.1

Chan Stop Cuts=-1
Use User Specified Reach Order=0
Composite Channel Slope=5